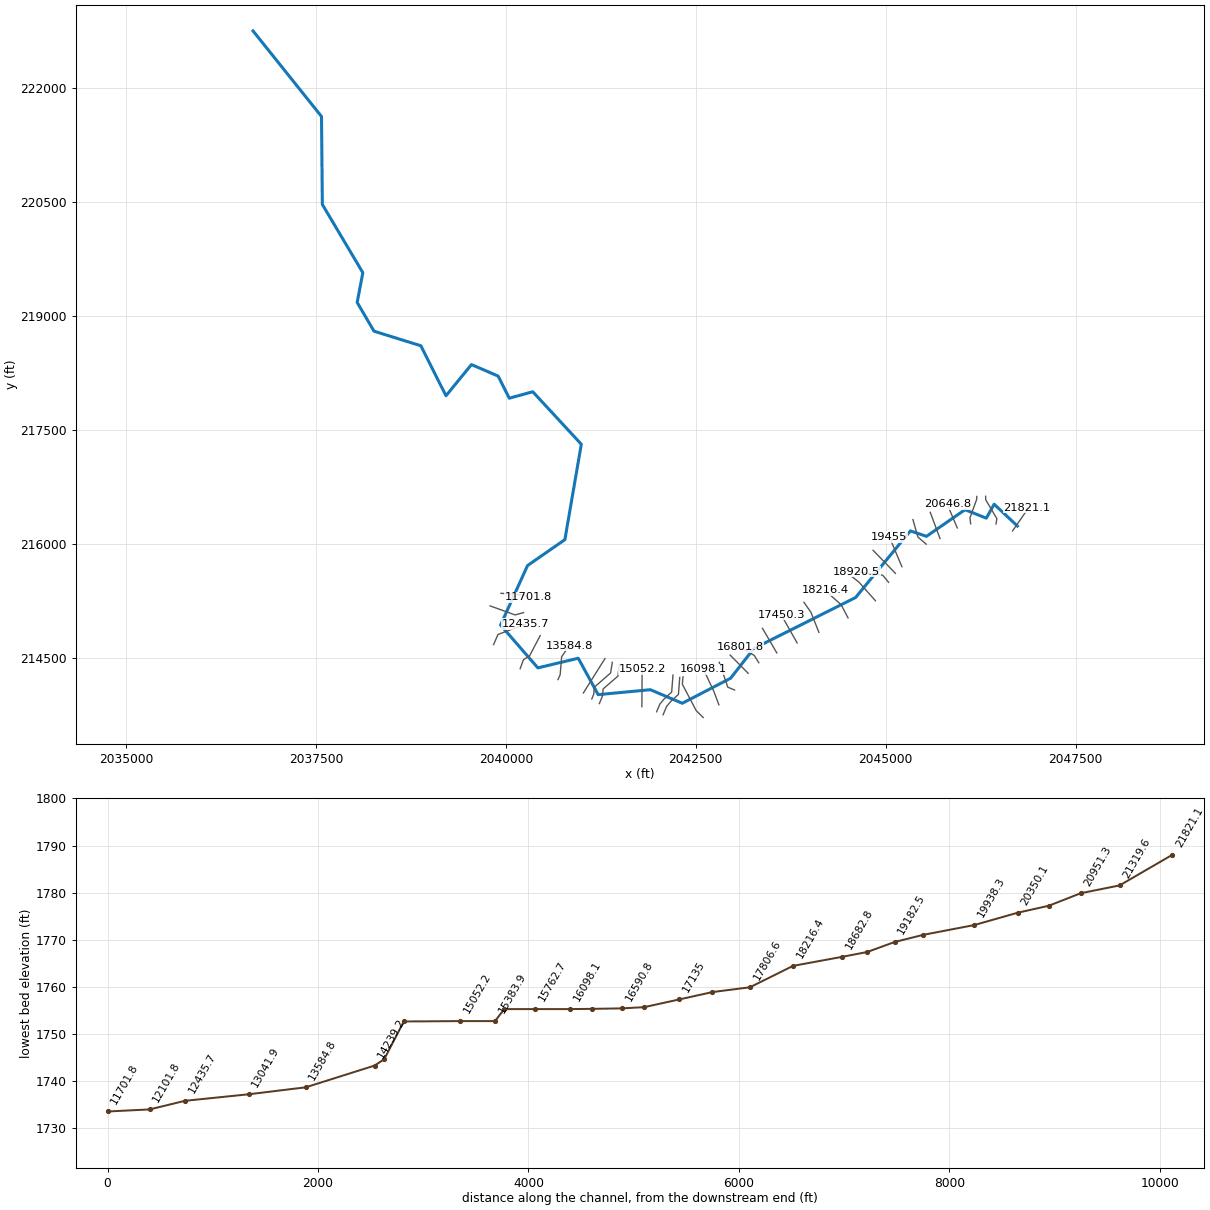
--- LTLSTNYCK.prj (project) ---

Proj Title=LTLSTNYCK
Current Plan=p01
Default Exp/Contr=0,0
English Units
Geom File=g01
Flow File=f01
Plan File=p01
BEGIN DESCRIPTION:
END DESCRIPTION:
DSS Export Rating Curves= 0
DSS Export Rating Curve Sorted= 0
DSS Export Volume Flow Curves= 0
DXF OffsetX= 0
DXF OffsetY= 0
DXF ScaleX= 0
DXF ScaleY= 0

--- LTLSTNYCK.p01 (plan) ---

Plan Title=Floodplain
Program Version=4.00
Geom File=g01
Flow File=f01
K Sum by GR=0
Std Step Tol=0.01
Critical Tol=0.01
Num of Std Step Trials=20
Max Error Tol=0.3
Flow Tol Ratio=0.001
Split Flow NTrial=30
Split Flow Tol=0.02
Split Flow Ratio=0.02
Log Output Level=0
Friction Slope Method=1
Unsteady Friction Slope Method=2
Unsteady Bridges Friction Slope Method=1
Global Log Level=0
CheckData=False
Run HTab=0
Run UNet=0
Run PostProcess=0
UNET Theta=0
UNET Theta Warmup=0
UNET ZTol=0
UNET ZSATol=0
UNET MxIter=0
UNET MaxInSteps=0
UNET DtIC=0
UNET DtMin=0
UNET MaxCRTS=0
UNET WFStab=0
UNET SFStab=0
UNET WFX=0
UNET SFX=0
UNET DSS MLevel=0
UNET DZMax Abort=0
UNET Convert EG Bridges=0
UNET Use Existing IB Tables=0
UNET Froude Limit=0
UNET Froude Power=0
Write IC File=0
Echo Input=False
Echo Output=False
Write Detailed=0

--- LTLSTNYCK.f01 (steady flow) ---

Flow Title=NFF Regression Equation
Program Version=4.10
Number of Profiles= 1
Profile Names=P100yr
River Rch & RM=LTLSTNYCK,Main            ,21821.1
519.8741
River Rch & RM=LTLSTNYCK,Main            ,20350.1
559.0784
River Rch & RM=LTLSTNYCK,Main            ,18920.5
586.6327
River Rch & RM=LTLSTNYCK,Main            ,15471.6
641.2244
River Rch & RM=LTLSTNYCK,Main            ,15052.2
731.5805
River Rch & RM=LTLSTNYCK,Main            ,12435.7
759.2076
River Rch & RM=LTLSTNYCK,Main            ,12101.8
878.9986
River Rch & RM=LTLSTNYCK,Main            ,6945.7
969.1659
River Rch & RM=LTLSTNYCK,Main            ,259.1
1073.876
Boundary for River Rch & Prof#=LTLSTNYCK,Main            , 1
Up Type= 0
Dn Type= 3
Dn Slope=0.01
DSS Import GetInterval= 0
DSS Import GetPeak= 0
DSS Import FillOption= 0

--- LTLSTNYCK.g01 (geometry) ---

Geom Title=USGS 1m DEM
Program Version=4.10

River Reach=LTLSTNYCK       ,Main
Reach XY= 30
     2046734.536      216239.001      2046428.98      216526.328
     2046325.345      216342.499     2046045.222      216454.079
     2045537.829      216103.485     2045325.829      216175.131
     2044604.087      215297.765     2043265.134      214627.114
     2042959.457      214235.463     2042323.377      213905.786
     2041902.805      214084.171     2041215.738      214019.501
     2040953.586      214498.668     2040421.989      214371.757
     2039931.148      214935.468     2040285.847      215718.731
     2040777.537      216059.623     2040993.789      217315.777
     2040354.606      218006.959     2040045.578      217921.542
     2039899.359      218212.771     2039547.619      218364.315
     2039212.244      217954.181     2038881.298       218612.06
     2038265.109      218803.908     2038043.147       219182.48
       2038117.8      219573.973     2037584.814      220471.976
      2037573.81      221630.396     2036672.564       222756.54

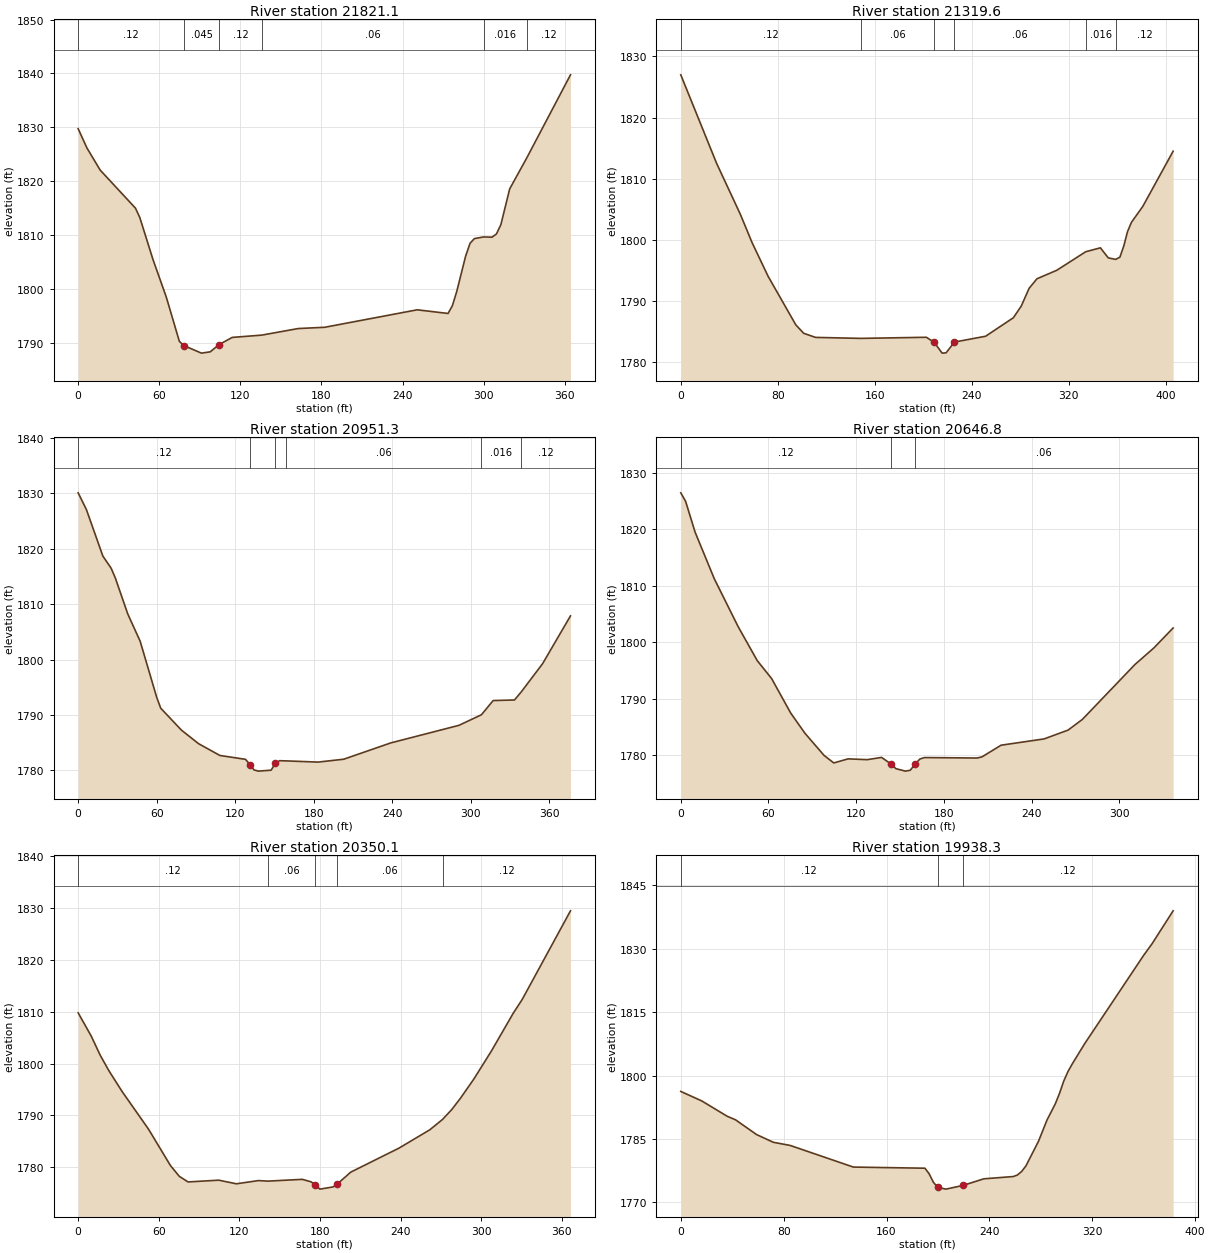
Type RM Length L Ch R = 1 ,21821.1 ,427.4,501.6,544.9
XS GIS Cut Line= 3
     2046670.934      216174.788     2046854.794      216439.793
     2046859.636      216481.293
#Sta/Elev= 30
       0 1829.73     6.5 1826.15    16.3 1822.04    42.4 1814.97    45.6 1813.24
    55.4  1805.4    65.2 1798.46    74.9 1790.21    78.2 1789.44    91.2 1788.03
    97.7 1788.27   104.3 1789.62     114 1790.95  135.821791.375   162.9  1792.6
   182.4 1792.83   250.9 1796.08   273.7  1795.4   276.9 1796.84   280.2 1799.54
   286.7 1806.05     290 1808.45   293.2 1809.31  300.04 1809.62   306.2 1809.57
   309.5 1810.17   312.8 1811.91   319.3 1818.54  331.971824.311   364.3 1839.74
#Mann= 6 ,-1 , 0
       0     .12       0    78.2    .045       0   104.3     .12       0
  135.82     .06       0  300.04    .016       0  331.97     .12       0
Bank Sta=78.2,104.3
XS Rating Curve= 0 ,0
Exp/Cntr=0.3,0.1

Type RM Length L Ch R = 1 ,21319.6 ,398.1,368.3,347.6
XS GIS Cut Line= 4
     2046453.428      216264.966     2046463.907      216336.221
     2046318.074      216583.617     2046316.395      216630.635
#Sta/Elev= 30
       0 1826.99    29.5 1812.56    49.1 1804.23    58.9 1799.55      72  1794.1
    94.9 1786.15   101.4 1784.77   111.2  1784.1  148.451783.938   202.6 1784.12
   209.1  1783.3   215.6 1781.53   218.9 1781.58   225.8 1783.34   251.5 1784.29
   274.4 1787.31   280.9 1789.21   287.4 1792.12   293.9 1793.68   310.2 1795.06
  334.111798.093   346.2 1798.73   352.7 1797.09  358.821796.841   362.3 1797.21
   365.5 1799.03   368.6 1801.39   371.8 1802.89   381.2  1805.5   406.2 1814.51
#Mann= 6 ,-1 , 0
       0     .12       0  148.45     .06       0   209.1    .045       0
   225.8     .06       0  334.11    .016       0  358.82     .12       0
Bank Sta=209.1,225.8
XS Rating Curve= 0 ,0
Exp/Cntr=0.3,0.1

Type RM Length L Ch R = 1 ,20951.3 ,274.9,304.5,332.5
XS GIS Cut Line= 4
     2046119.236      216268.296      2046109.74      216346.638
     2046198.282      216588.825     2046199.746      216628.339
#Sta/Elev= 30
       0 1830.11     6.3 1827.09    18.9 1818.69    25.2 1816.51    28.4 1814.75
    37.9 1808.26    47.4 1803.32      60 1793.23    63.1 1791.24    78.9 1787.29
      92 1784.84   108.3 1782.71   127.9 1782.01   131.4 1781.05   134.4  1780.1
   137.7 1779.88   147.5 1780.05   150.7  1781.3     154 1781.76   159.21781.725
   183.4 1781.51     203 1782.03   238.9 1784.97   291.1 1788.15  308.221790.052
   317.2 1792.62   333.5 1792.72  338.751794.203     355 1799.28   376.3  1807.9
#Mann= 6 ,-1 , 0
       0     .12       0   131.4    .045       0   150.7     .12       0
   159.2     .06       0  308.22    .016       0  338.75     .12       0
Bank Sta=131.4,150.7
XS Rating Curve= 0 ,0
Exp/Cntr=0.3,0.1

Type RM Length L Ch R = 1 ,20646.8 ,303.6,296.6,288.7
XS GIS Cut Line= 2
     2045943.074      216213.825     2045812.025      216524.205
#Sta/Elev= 30
       0 1826.48     3.3 1824.98     9.8 1819.52    22.9 1811.29    39.2 1802.82
    52.3 1796.79    62.2 1793.59    75.2 1787.51      85 1783.91    98.1 1779.99
   104.7 1778.67   114.5 1779.39   127.6 1779.25   137.4 1779.65   143.6 1778.53
   147.2 1777.66   153.7 1777.22     157 1777.37   160.3 1778.44   163.6 1779.36
   166.8 1779.62   202.8 1779.54   206.1 1779.74   219.2 1781.81   248.6 1782.92
     265 1784.48   274.8 1786.37   310.7 1796.07   323.8 1799.04   336.9 1802.56
#Mann= 3 ,-1 , 0
       0     .12       0   143.6    .045       0   160.3     .06       0
Bank Sta=143.6,160.3
XS Rating Curve= 0 ,0
Exp/Cntr=0.3,0.1

Type RM Length L Ch R = 1 ,20350.1 ,361.3,411.8,362.5
XS GIS Cut Line= 2
     2045715.725      216075.404     2045587.581      216418.736
#Sta/Elev= 30
       0 1809.79     9.8 1805.27    16.4 1801.61    22.9  1798.6    32.7  1794.6
    52.4 1787.31    68.7 1780.29    75.3  1778.2    81.8 1777.12   104.7 1777.46
   117.8 1776.76   134.2 1777.38  141.261777.277   166.9 1777.62   173.4 1777.14
   176.4 1776.56     180 1775.73   189.8 1776.16     193 1776.73   202.9 1779.01
   238.9 1783.66   261.8  1787.2  271.251789.195   278.1  1791.1   284.7 1793.33
   294.5 1796.98   307.6  1802.4   323.9 1809.72   330.5 1812.35   366.5  1829.5
#Mann= 5 ,-1 , 0
       0     .12       0  141.26     .06       0   176.4    .045       0
     193     .06       0  271.25     .12       0
Bank Sta=176.4,193
XS Rating Curve= 0 ,0
Exp/Cntr=0.3,0.1

Type RM Length L Ch R = 1 ,19938.3 ,477,483.3,482.2
XS GIS Cut Line= 3
      2045534.22      216000.283     2045424.845      216094.033
     2045359.225      216323.702
#Sta/Elev= 30
       0 1796.24    16.4 1793.98      36 1790.38    42.6 1789.52    58.9 1786.04
      72  1784.2    85.1 1783.46   134.2 1778.34   189.9 1778.07   193.1 1776.78
   196.4 1774.78   199.7 1773.55   206.2 1773.12   219.3 1773.98   235.7 1775.56
   258.6  1776.1   261.8 1776.46   265.1  1777.3   268.4  1778.6   278.2 1784.44
   284.8 1789.46   291.3 1793.32   294.6 1795.82   297.8 1798.66   301.1 1800.93
   304.4 1802.72   314.2 1807.58     360 1828.45   366.6 1831.22   382.9 1838.98
#Mann= 3 ,-1 , 0
       0     .12       0   199.7    .045       0   219.3     .12       0
Bank Sta=199.7,219.3
XS Rating Curve= 0 ,0
Exp/Cntr=0.3,0.1

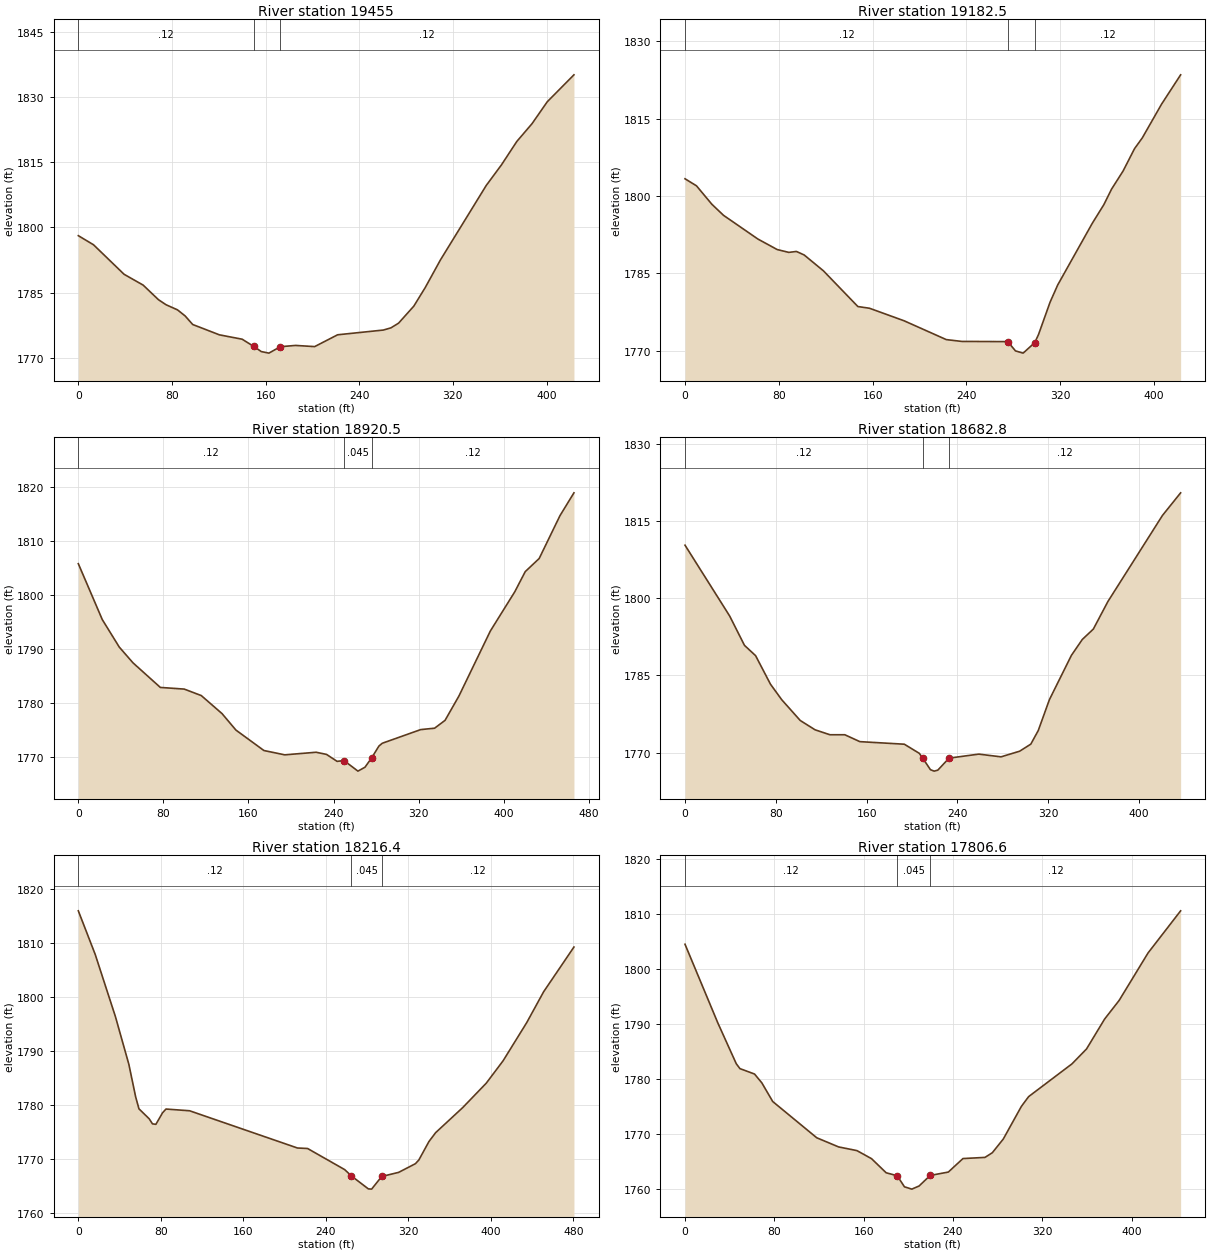
Type RM Length L Ch R = 1 ,19455   ,258.2,272.5,282.6
XS GIS Cut Line= 2
     2045214.149      215703.811     2045049.845      216094.033
#Sta/Elev= 30
       0 1798.08      13 1795.98    39.1 1789.19    55.4  1786.7    68.4 1783.36
    74.9 1782.19    84.7 1781.01    91.2 1779.62    97.7 1777.64   120.5 1775.26
     140 1774.25   149.8  1772.6   156.3 1771.41   162.8 1771.05   172.6 1772.53
   185.6 1772.82   201.9 1772.55   221.5 1775.27   260.6 1776.36   267.1 1776.87
   273.6 1777.95   286.6 1781.86   296.4 1786.16   309.4 1792.52   348.5 1809.64
   361.5 1814.38   374.6 1819.76   387.6 1823.85   400.6 1828.89   423.4 1835.09
#Mann= 3 ,-1 , 0
       0     .12       0   149.8    .045       0   172.6     .12       0
Bank Sta=149.8,172.6
XS Rating Curve= 0 ,0
Exp/Cntr=0.3,0.1

Type RM Length L Ch R = 1 ,19182.5 ,241.7,262,284.7
XS GIS Cut Line= 2
      2045128.38      215616.392     2044834.541      215920.191
#Sta/Elev= 30
       0 1803.33     9.8 1801.96    22.9 1798.39    32.8 1796.25    62.2 1791.64
    78.6 1789.61    88.5 1789.06      95 1789.24   101.6 1788.56     118 1785.49
   147.4 1778.56   157.3 1778.23   186.8  1775.8   222.8 1772.15   235.9  1771.8
   275.2 1771.76   281.8 1769.96   288.3 1769.53   298.2 1771.56   301.4 1773.12
   311.3 1779.42   317.8 1782.75   347.3 1794.71   357.1  1798.3   363.7 1801.32
   373.5 1804.82   383.3 1809.17   389.9 1811.25   406.3 1817.78   422.6 1823.48
#Mann= 3 ,-1 , 0
       0     .12       0   275.2    .045       0   298.2     .12       0
Bank Sta=275.2,298.2
XS Rating Curve= 0 ,0
Exp/Cntr=0.3,0.1

Type RM Length L Ch R = 1 ,18920.5 ,259.8,237.7,208.3
XS GIS Cut Line= 3
     2045039.428      215497.679     2044961.303      215591.429
     2044620.157        215635.7
#Sta/Elev= 30
       0 1805.86    22.5 1795.51    38.5  1790.4    51.4 1787.48    77.1 1782.92
    99.6 1782.61   115.6 1781.41   135.1 1778.07   148.2 1775.01   174.5 1771.22
   194.1 1770.42   223.6  1770.9   233.4  1770.5   243.3 1769.21   249.8 1769.36
   262.9  1767.4   269.5 1768.12     276 1769.91   282.6 1772.04   285.8 1772.57
   321.9  1775.1     335 1775.36   344.8 1776.81   357.9 1781.34   387.4 1793.38
   410.4 1800.66   420.2 1804.39   433.3 1806.82   452.9 1814.78     466    1819
#Mann= 3 ,-1 , 0
       0     .12       0   249.8    .045       0     276     .12       0
Bank Sta=249.8,276
XS Rating Curve= 0 ,0
Exp/Cntr=0.3,0.1

Type RM Length L Ch R = 1 ,18682.8 ,458.5,466.4,451.2
XS GIS Cut Line= 3
     2044865.697      215255.369     2044646.199      215502.888
     2044562.865      215567.992
#Sta/Elev= 30
       0 1810.36    39.3 1796.59    52.4 1790.86    62.2 1788.85    75.3  1783.3
    85.2 1780.28   101.5 1776.24   114.6 1774.42   127.7 1773.46   140.8 1773.46
     154 1772.12   193.2 1771.62   206.4 1769.84   209.6 1768.85   216.2 1766.66
   219.5 1766.38   222.7 1766.57   232.6 1768.91   258.8 1769.69   278.4 1769.16
   294.8 1770.26   304.6 1771.63   311.2 1774.29     321 1780.29   340.4 1788.92
     350 1792.01   359.7 1794.03   372.5 1799.38   420.6 1816.15   436.6 1820.55
#Mann= 3 ,-1 , 0
       0     .12       0   209.6    .045       0   232.6     .12       0
Bank Sta=209.6,232.6
XS Rating Curve= 0 ,0
Exp/Cntr=0.3,0.1

Type RM Length L Ch R = 1 ,18216.4 ,426.8,409.8,390.8
XS GIS Cut Line= 3
     2044505.257      215029.536     2044414.428      215203.408
     2044201.457        215391.9
#Sta/Elev= 30
       0 1815.96    16.4 1807.88      36 1796.37      49 1787.56    55.6 1781.53
    58.8 1779.32    68.7 1777.48    71.9 1776.54    75.2 1776.45    81.7 1778.59
      85 1779.28   107.9 1778.96   212.5 1772.07   222.3 1771.98   258.3 1768.07
   264.8  1766.9   281.2 1764.51   284.4 1764.46   294.2  1766.8   310.6 1767.56
   326.9 1769.17   330.2 1769.85     340 1773.27   346.5 1774.91   372.7 1779.54
   395.6 1784.07   411.9 1788.21   434.8 1795.27   451.2 1800.98   480.6 1809.26
#Mann= 3 ,-1 , 0
       0     .12       0   264.8    .045       0   294.2     .12       0
Bank Sta=264.8,294.2
XS Rating Curve= 0 ,0
Exp/Cntr=0.3,0.1

Type RM Length L Ch R = 1 ,17806.6 ,350.1,356.3,361.2
XS GIS Cut Line= 3
      2044121.45      214839.575      2044015.99       215104.45
     2043924.845      215234.658
#Sta/Elev= 30
       0 1804.54    29.5 1790.16    45.9 1782.78    49.2 1781.88    62.3 1780.89
    68.8 1779.29    78.6 1775.88     118 1769.28   137.6 1767.61     154 1766.94
   167.1 1765.47   180.2  1762.9   190.1 1762.36   196.6 1760.34   203.2 1759.92
   209.7 1760.49   219.6 1762.41   235.9 1763.03     249 1765.49   268.7  1765.7
   275.3 1766.55   285.1 1769.04   301.3 1774.98   307.8 1776.77   346.7 1782.75
   359.7 1785.46   375.9 1790.91   388.9  1794.3   414.8 1802.95     444 1810.63
#Mann= 3 ,-1 , 0
       0     .12       0   190.1    .045       0   219.6     .12       0
Bank Sta=190.1,219.6
XS Rating Curve= 0 ,0
Exp/Cntr=0.3,0.1

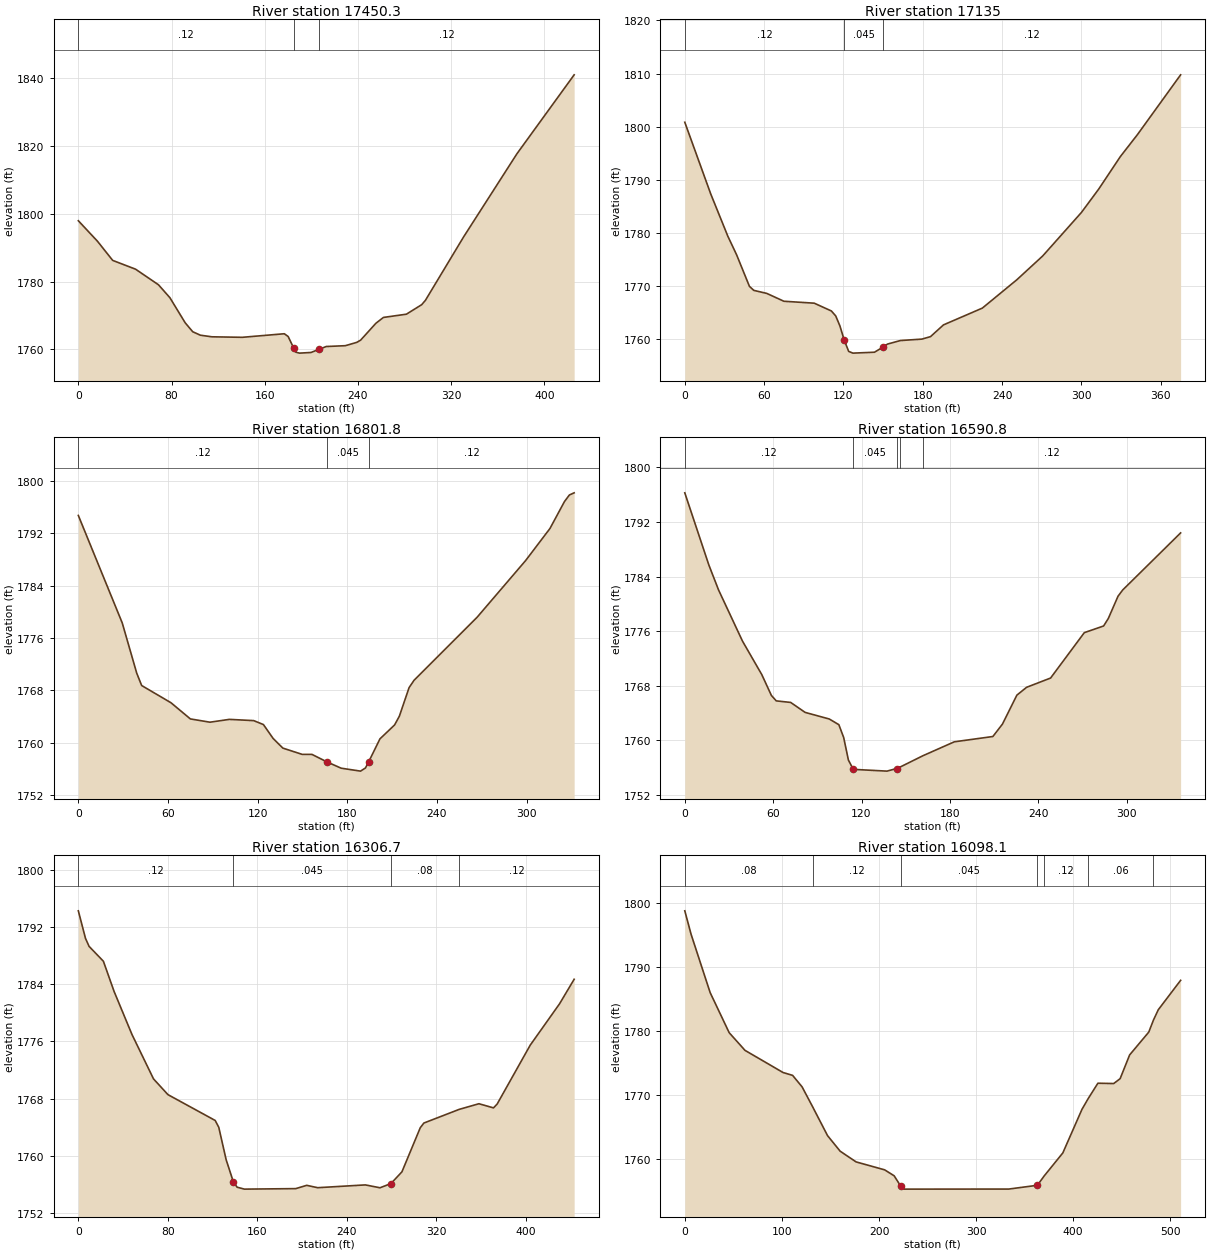
Type RM Length L Ch R = 1 ,17450.3 ,314.5,315.2,315.3
XS GIS Cut Line= 2
     2043834.878      214700.116     2043625.365      215070.596
#Sta/Elev= 30
       0 1797.91    16.4 1791.88    29.5 1786.22    49.1 1783.64    68.8 1779.04
    78.6 1775.23    91.7 1767.85    98.2  1765.2   104.8 1764.18   114.6 1763.71
   140.8 1763.56   176.8 1764.61   180.1  1763.8   184.9 1760.36   186.6 1759.18
   189.9  1758.9   199.7 1759.09   206.3 1759.98   212.8 1760.85   229.2 1761.09
     239 1762.07   242.3 1762.72   255.4 1767.69   261.9 1769.42   281.6 1770.37
   294.7 1773.17   297.9 1774.44   330.7 1793.14   376.5 1817.65   425.6  1840.9
#Mann= 3 ,-1 , 0
       0     .12       0   184.9    .045       0   206.3     .12       0
Bank Sta=184.9,206.3
XS Rating Curve= 0 ,0
Exp/Cntr=0.3,0.1

Type RM Length L Ch R = 1 ,17135   ,312.8,333.2,352.7
XS GIS Cut Line= 2
     2043567.591      214568.358      2043378.79      214892.526
#Sta/Elev= 30
       0 1800.83    19.6 1787.34    32.6 1779.34    39.2 1775.86    48.9 1769.92
    52.2 1769.16      62 1768.59      75 1767.11    97.9 1766.75   110.9 1765.28
   114.2 1764.34   117.4 1762.43   120.7 1759.72     124 1757.66   127.2 1757.34
   143.5 1757.51   150.1  1758.5   153.3 1759.04   163.1 1759.71   179.4 1759.98
   185.9 1760.45   195.7 1762.66   225.1 1765.82   251.2 1771.16   270.8 1775.65
   300.1 1783.85   313.2 1788.26   329.5 1794.36   342.5 1798.52   375.1 1809.76
#Mann= 3 ,-1 , 0
       0     .12       0   120.7    .045       0   150.1     .12       0
Bank Sta=120.7,150.1
XS Rating Curve= 0 ,0
Exp/Cntr=0.3,0.1

Type RM Length L Ch R = 1 ,16801.8 ,220.9,211,200.8
XS GIS Cut Line= 3
      2043330.57      214439.419     2043269.893      214536.123
      2043081.01      214644.475
#Sta/Elev= 30
       0 1794.68    29.4 1778.29    39.1 1770.63    42.4 1768.75      62 1766.13
      75 1763.66    88.1 1763.16   101.1 1763.59   117.4  1763.4   123.9  1762.8
   130.4 1760.68   136.9 1759.21   149.9 1758.25   156.4 1758.25   166.2 1757.13
   175.9 1756.15   188.9  1755.7   192.2 1756.18   194.3 1757.09   201.9 1760.62
   211.7 1762.74   214.9 1764.08   221.4 1768.43   224.7 1769.54   266.9 1779.15
   299.4  1787.8   315.7 1792.69   325.4 1796.79   328.7  1797.8   331.9 1798.13
#Mann= 3 ,-1 , 0
       0     .12       0   166.2    .045       0   194.3     .12       0
Bank Sta=166.2,194.3
XS Rating Curve= 0 ,0
Exp/Cntr=0.3,0.1

Type RM Length L Ch R = 1 ,16590.8 ,301.4,284.2,267.4
XS GIS Cut Line= 2
     2043190.254      214300.999     2042953.041      214539.894
#Sta/Elev= 30
       0 1796.28    16.3 1785.71    22.9 1782.04    39.2 1774.51    52.3  1769.6
    58.8 1766.55    62.1 1765.75    71.9 1765.52    81.7 1764.06    98.1 1763.09
   104.6 1762.26   107.9 1760.37   111.1 1757.07   114.4  1755.7   137.3 1755.44
   143.8 1755.82  146.191756.037  161.651757.693     183 1759.74   209.2 1760.52
   215.7 1762.34   225.5 1766.59   232.1 1767.74   248.4  1769.1   271.3 1775.76
   284.4 1776.74   287.6 1777.84   294.2 1781.11   297.4 1782.03   336.7  1790.4
#Mann= 5 ,-1 , 0
       0     .12       0   114.4    .045       0   143.8     .12       0
  146.19     .08       0  161.65     .12       0
Bank Sta=114.4,143.8
XS Rating Curve= 0 ,0
Exp/Cntr=0.3,0.1

Type RM Length L Ch R = 1 ,16306.7 ,204.1,208.5,212
XS GIS Cut Line= 3
     2043011.665      214080.338     2042922.894       214117.07
     2042809.621      214445.057
#Sta/Elev= 30
       0 1794.25     6.4  1790.4     9.6 1789.28    22.4  1787.2      32 1782.96
      48 1776.94    67.2 1770.75    80.1 1768.55   122.3 1764.94   125.5 1763.99
   132.1 1759.45   138.6 1756.33   141.9 1755.61   148.4 1755.34   194.3 1755.41
   204.1 1755.87   213.9 1755.54   256.5 1755.93   269.6 1755.53   279.4 1756.12
   289.2 1757.76   305.6 1763.93   308.8 1764.58  340.35 1766.49     358 1767.28
     371  1766.7   374.3 1767.24   403.8 1775.46     430 1781.24   443.1 1784.68
#Mann= 4 ,-1 , 0
       0     .12       0   138.6    .045       0   279.4     .08       0
  340.35     .12       0
Bank Sta=138.6,279.4
XS Rating Curve= 0 ,0
Exp/Cntr=0.3,0.1

Type RM Length L Ch R = 1 ,16098.1 ,333.7,335.4,336.7
XS GIS Cut Line= 3
     2042804.907      213885.528      2042737.07      214065.874
     2042601.564      214353.411
#Sta/Elev= 30
       0 1798.73     6.5 1795.06    26.1 1785.97    45.7 1779.71      62 1776.95
   101.2 1773.49     111 1773.05   120.8 1771.25  131.671768.136     147 1763.64
     160 1761.21   176.4 1759.54   205.8  1758.3   215.6 1757.37   222.2 1755.79
   225.4 1755.29   333.6  1755.3   363.1 1755.89  370.031757.336   389.3 1760.94
     409 1767.74  415.321769.399   425.4 1771.82   441.7 1771.77   448.3 1772.53
   458.1 1776.24   477.8  1779.8  482.641781.684   487.6 1783.29   510.6 1787.88
#Mann= 7 ,-1 , 0
       0     .08       0  131.67     .12       0   222.2    .045       0
   363.1     .04       0  370.03     .12       0  415.32     .06       0
  482.64     .12       0
Bank Sta=222.2,363.1
XS Rating Curve= 0 ,0
Exp/Cntr=0.3,0.1

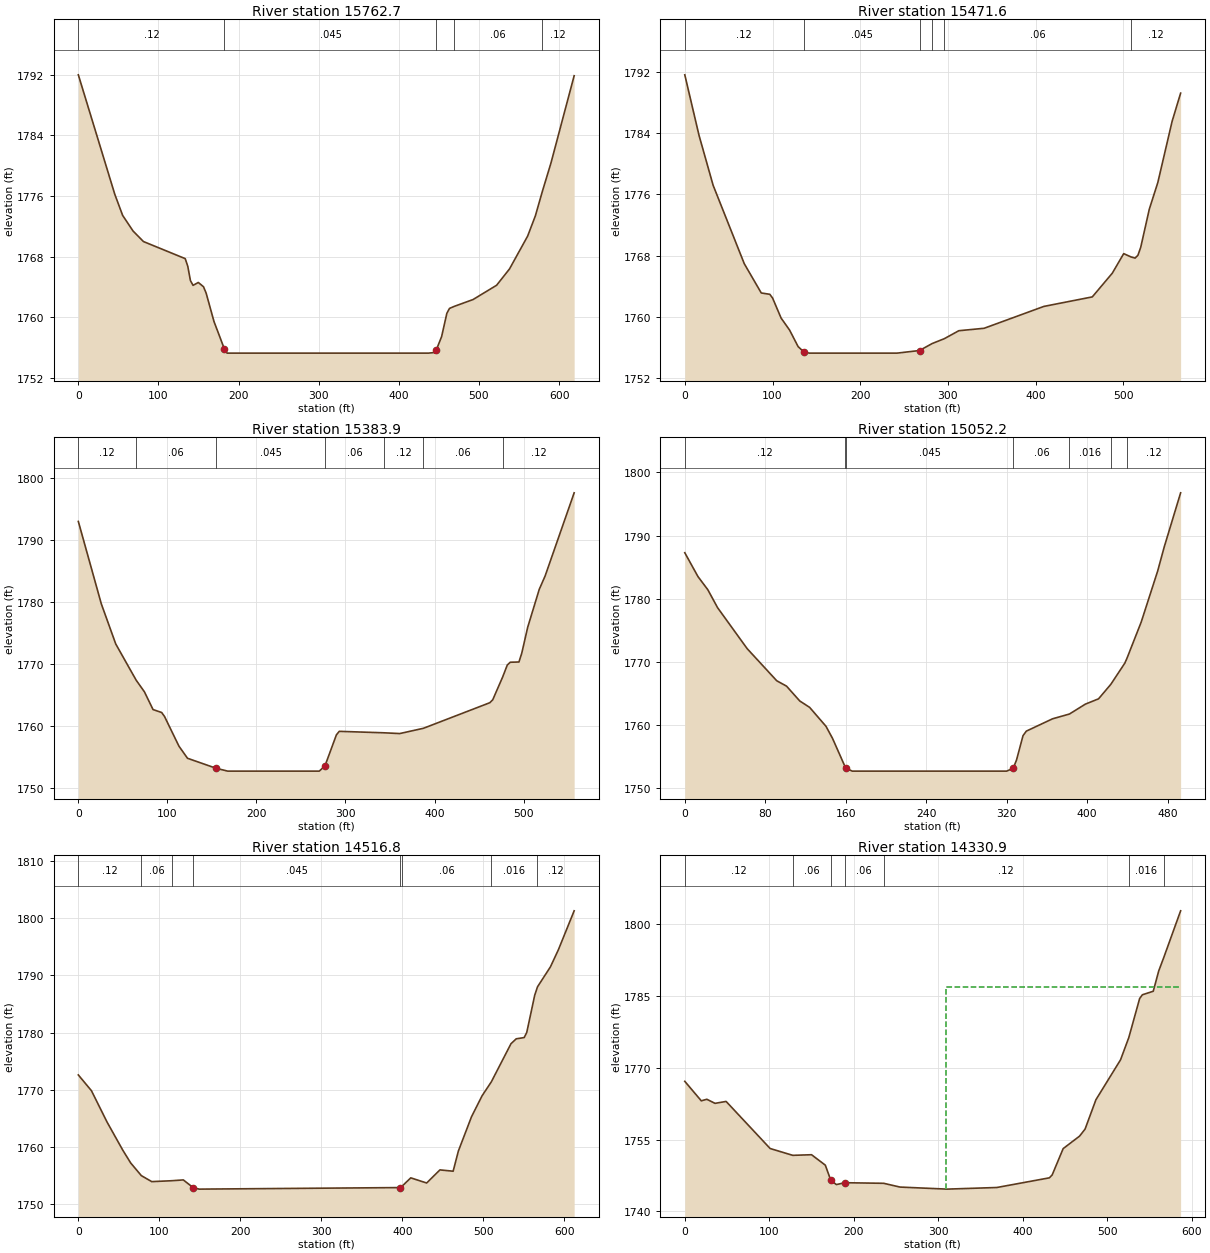
Type RM Length L Ch R = 1 ,15762.7 ,336,291.2,246.4
XS GIS Cut Line= 4
     2042598.469      213718.609     2042505.738      213809.891
     2042323.706       214156.89     2042332.573      214253.328
#Sta/Elev= 30
       0 1791.96    45.5 1776.22    55.3 1773.44    68.3 1771.38    81.3 1769.99
   133.4 1767.74   136.6 1766.73   139.9 1764.85   143.2 1764.22   149.7  1764.6
   156.2 1764.04   159.5  1763.2   169.3 1759.46   182.4  1755.8   185.6 1755.29
   437.1 1755.29   443.6 1755.36   446.9 1755.75   453.4 1757.47   459.9 1760.53
   463.2 1761.18   469.21761.451   492.6 1762.35     522 1764.23   538.1 1766.38
   560.7  1770.7   570.4 1773.38  578.961776.544   589.8 1780.32   618.8 1791.84
#Mann= 5 ,-1 , 0
       0     .12       0   182.4    .045       0   446.9     .12       0
   469.2     .06       0  578.96     .12       0
Bank Sta=182.4,446.9
XS Rating Curve= 0 ,0
Exp/Cntr=0.3,0.1

Type RM Length L Ch R = 1 ,15471.6 ,87.7,87.7,83.7
XS GIS Cut Line= 5
       2042070.8      213754.656     2042117.023       213864.88
     2042179.597      213938.831     2042272.509      214022.262
     2042289.691      214245.632
#Sta/Elev= 30
       0 1791.57    16.2 1783.69    32.3 1777.17    67.8 1766.95    87.2 1763.13
    96.9 1762.96   100.1 1762.47   109.8 1759.86   119.5 1758.29   129.2 1756.14
   135.7 1755.45   142.1 1755.29     242 1755.29   267.6 1755.63  282.051756.541
  295.981757.178   312.4 1758.21   341.3 1758.53   409.4 1761.38   464.6 1762.62
   487.4 1765.71   500.4 1768.26  508.831767.825   513.4 1767.68   516.6 1768.04
   519.8 1769.08   529.6 1774.06   539.3 1777.53   555.6 1785.51   565.3 1789.18
#Mann= 6 ,-1 , 0
       0     .12       0   135.7    .045       0   267.6     .06       0
  282.05     .12       0  295.98     .06       0  508.83     .12       0
Bank Sta=135.7,267.6
XS Rating Curve= 0 ,0
Exp/Cntr=0.3,0.1

Type RM Length L Ch R = 1 ,15383.9 ,305.4,331.7,362
XS GIS Cut Line= 5
     2041985.473      213794.038     2042027.903      213895.219
     2042090.477      213969.169     2042183.389      214052.601
     2042200.675      214277.315
#Sta/Elev= 30
       0 1792.96    25.8 1779.69      42 1773.23   64.931767.393    74.2 1765.52
    83.9 1762.66    93.6 1762.18    96.8 1761.54     113 1756.76   122.6 1754.81
   154.9 1753.19   167.8 1752.74   270.6 1752.74     277  1753.6   289.8 1758.58
     293 1759.15  343.541758.912   360.9 1758.79  387.591759.642   462.1 1763.76
   465.4 1764.24  476.451767.885   481.7 1769.83     485 1770.28   494.8 1770.32
     498 1771.76   504.6  1775.9   517.6 1782.02   524.2 1784.18   556.8 1797.57
#Mann= 7 ,-1 , 0
       0     .12       0   64.93     .06       0   154.9    .045       0
     277     .06       0  343.54     .12       0  387.59     .06       0
  476.45     .12       0
Bank Sta=154.9,277
XS Rating Curve= 0 ,0
Exp/Cntr=0.3,0.1

Type RM Length L Ch R = 1 ,15052.2 ,543.4,535.4,531.9
XS GIS Cut Line= 2
      2041791.08      213860.318     2041794.366      214353.333
#Sta/Elev= 30
       0 1787.29    13.1 1783.52    22.9 1781.44    32.6  1778.6      62 1772.12
    91.4 1767.04   101.2 1766.18   114.3 1763.84   124.1 1762.83   140.4 1759.83
   146.9 1757.92  159.521753.377     160 1753.23   166.5 1752.74     320 1752.74
   326.5 1753.18   329.8 1754.48   336.3 1758.35   339.6 1759.07   365.7 1761.02
   382.51761.778   398.3 1763.34   411.4 1764.18  423.621766.476   437.5 1769.82
  439.591770.567   453.8 1776.32   470.2 1784.41   476.7 1788.21     493 1796.77
#Mann= 7 ,-1 , 0
       0     .12       0  159.52     .06       0     160    .045       0
   326.5     .06       0   382.5    .016       0  423.62     .06       0
  439.59     .12       0
Bank Sta=160,326.5
XS Rating Curve= 0 ,0
Exp/Cntr=0.3,0.1

Type RM Length L Ch R = 1 ,14516.8 ,162.7,185.9,146.1
XS GIS Cut Line= 5
     2041231.521      213901.534     2041273.229        214003.3
     2041280.813      214094.316     2041476.119      214263.075
     2041493.184      214414.769
#Sta/Elev= 30
       0 1772.61    16.2 1769.85    35.6 1764.34      55 1759.44    64.7 1757.22
   77.781755.018    90.6 1753.97  115.521754.128   129.6 1754.27   141.8 1752.92
   149.1 1752.66   397.4 1752.93  399.181753.108   410.4 1754.63     430 1753.73
   446.4 1756.02   462.7 1755.79   469.2 1759.33   485.4 1765.31   498.4 1768.96
  509.861771.404   534.1 1778.06   540.6 1778.92   550.4 1779.14   553.6 1780.04
   563.4 1786.53  566.821787.993   582.8 1791.49   592.6 1794.47   612.1 1801.28
#Mann= 8 ,-1 , 0
       0     .12       0   77.78     .06       0  115.52     .12       0
   141.8    .045       0   397.4     .04       0  399.18     .06       0
  509.86    .016       0  566.82     .12       0
Bank Sta=141.8,397.4
XS Rating Curve= 0 ,0
Exp/Cntr=0.3,0.1

Type RM Length L Ch R = 1 ,14330.9 ,128.7,91.7,102.5
XS GIS Cut Line= 5
     2041131.622      213962.761     2041157.562      214026.054
     2041165.147       214117.07     2041379.414      214304.791
     2041402.168      214445.107
#Sta/Elev= 30
       0 1767.19    19.5 1763.12    26.1 1763.44    35.8 1762.59    48.9 1762.99
     101 1753.15  127.761751.722     150 1751.85   166.3 1749.67   172.8  1746.5
   179.4 1745.61   189.2    1746  235.351745.878   254.7 1745.09   310.4 1744.66
   369.3    1745   431.5 1747.02   434.8 1747.63   447.8 1753.13   467.2 1755.74
   473.7  1757.2   486.6 1763.36   515.7 1771.69  525.471776.337   538.3  1784.5
   541.5 1785.28   554.4 1786.02   560.9 1790.28  566.821793.057   586.8 1802.83
#Mann= 7 ,-1 , 0
       0     .12       0  127.76     .06       0   172.8    .045       0
   189.2     .06       0  235.35     .12       0  525.47    .016       0
  566.82     .12       0
#XS Ineff= 2 , 0
                          309.46         1786.96
Permanent Ineff=
       F       F
Bank Sta=172.8,189.2
XS Rating Curve= 0 ,0
Exp/Cntr=0.3,0.1

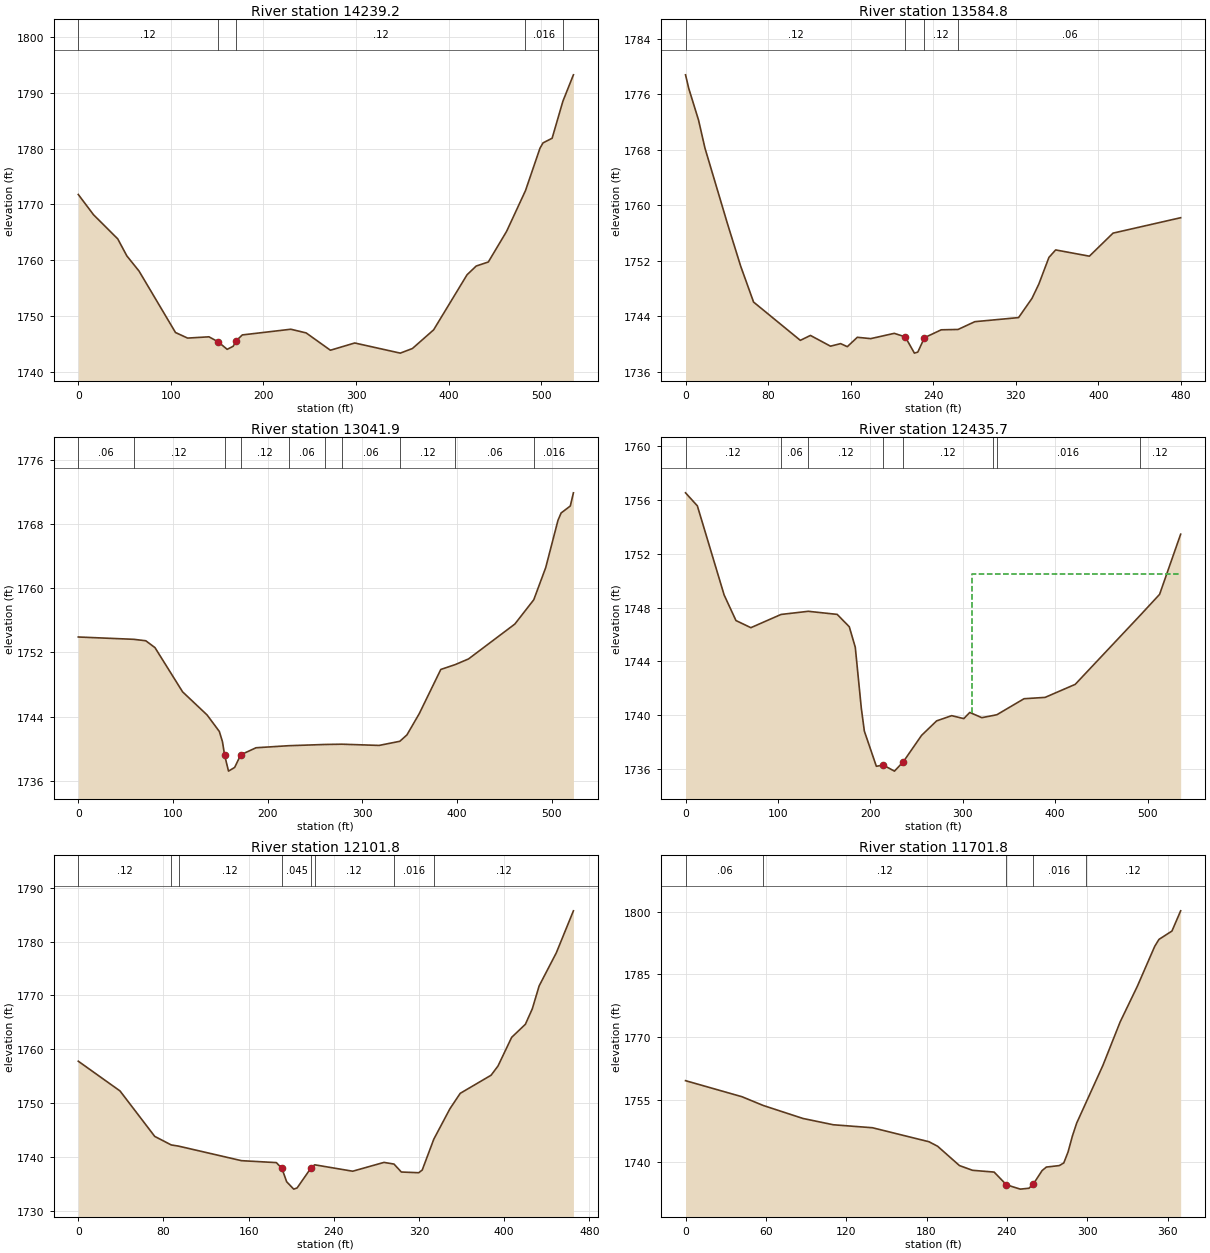
Type RM Length L Ch R = 1 ,14239.2 ,659.2,654.4,662.2
XS GIS Cut Line= 2
     2041021.065      214041.544     2041305.464      214494.408
#Sta/Elev= 30
       0 1771.79    16.4 1768.16    42.6 1763.82    52.5 1760.75    65.6 1758.04
     105    1747   118.1    1746   141.1 1746.23   150.9 1745.35   160.8 1743.98
   167.3 1744.53   170.6 1745.53   177.2 1746.57   229.6 1747.59   246.1 1746.93
   272.3 1743.82   298.6 1745.12   347.8  1743.3   360.9 1744.13   383.8 1747.48
   419.9 1757.37   429.8 1758.94   442.9 1759.67   462.6 1765.16  483.011772.477
   498.7 1780.11     502 1781.06   511.8 1781.89  523.381788.515   534.8 1793.28
#Mann= 5 ,-1 , 0
       0     .12       0   150.9    .045       0   170.6     .12       0
  483.01    .016       0  523.38     .12       0
Bank Sta=150.9,170.6
XS Rating Curve= 0 ,0
Exp/Cntr=0.3,0.1

Type RM Length L Ch R = 1 ,13584.8 ,571.1,542.9,510.4
XS GIS Cut Line= 4
     2040687.313      214217.567     2040715.755      214283.933
     2040734.717      214517.162      2040831.94      214660.681
#Sta/Elev= 30
       0 1778.79     3.1 1776.84    12.6 1772.27    18.8 1768.24    40.8 1757.25
    53.4 1751.23    65.9 1746.05   111.2 1740.53     121 1741.24   140.4 1739.69
   150.2 1740.06   156.7 1739.62   166.4 1740.97   179.4 1740.78   202.2 1741.54
   212.8 1741.03   221.7 1738.69     225 1738.84   231.4 1740.91   247.7 1742.05
  264.011742.101   280.2 1743.22   322.6 1743.81   335.6 1746.58   342.2 1748.63
     352 1752.48   358.5 1753.56   391.2 1752.66   414.1 1755.98   479.6  1758.2
#Mann= 4 ,-1 , 0
       0     .12       0   212.8    .045       0   231.4     .12       0
  264.01     .06       0
Bank Sta=212.8,231.4
XS Rating Curve= 0 ,0
Exp/Cntr=0.3,0.1

Type RM Length L Ch R = 1 ,13041.9 ,609.5,606.1,580.5
XS GIS Cut Line= 4
     2040188.711      214360.543     2040232.233      214479.238
     2040311.872      214528.539     2040452.719      214796.819
#Sta/Elev= 30
       0 1753.91   58.651753.621    71.3 1753.44      81 1752.59   110.2 1747.08
   136.1  1744.2     149 1742.15   152.3 1740.88   154.6  1739.2   158.7 1737.21
   165.2 1737.67   171.6 1739.24   187.8 1740.12  222.311740.375  260.641740.528
  278.481740.562   317.8 1740.41  339.661740.923   347.2 1741.72   360.2 1744.36
     383 1749.87  398.231750.474   412.3 1751.18   461.2 1755.52  481.221758.548
   493.8 1762.54   506.8 1768.44   510.1 1769.35   519.8 1770.22   523.1 1771.86
#Mann= 10 ,-1 , 0
       0     .06       0   58.65     .12       0   154.6    .045       0
   171.6     .12       0  222.31     .06       0  260.64     .12       0
  278.48     .06       0  339.66     .12       0  398.23     .06       0
  481.22    .016       0
Bank Sta=154.6,171.6
XS Rating Curve= 0 ,0
Exp/Cntr=0.3,0.1

Type RM Length L Ch R = 1 ,12435.7 ,356.1,333.9,313
XS GIS Cut Line= 3
     2039839.237      214678.391     2039896.611      214811.068
     2040262.571      214949.488
#Sta/Elev= 30
       0 1756.54    12.8 1755.57    41.8 1748.93    54.6 1747.03    70.7  1746.5
  103.351747.485  132.821747.719   164.1 1747.49   177.2 1746.57   183.7 1745.04
   190.2 1740.52   193.5  1738.8   206.5 1736.18   213.9 1736.27   226.1 1735.82
   235.8 1736.53   255.4 1738.48   271.7 1739.56     288 1739.95   301.1 1739.73
   307.6 1740.19   320.6  1739.8  332.461739.956  336.971740.021   366.3 1741.21
   389.1 1741.31   421.7 1742.28  491.781747.403     513 1748.98   535.8 1753.46
#Mann= 8 ,-1 , 0
       0     .12       0  103.35     .06       0  132.82     .12       0
   213.9    .045       0   235.8     .12       0  332.46     .06       0
  336.97    .016       0  491.78     .12       0
#XS Ineff= 2 , 0
                          309.46          1750.5
Permanent Ineff=
       F       F
Bank Sta=213.9,235.8
XS Rating Curve= 0 ,0
Exp/Cntr=0.3,0.1

Type RM Length L Ch R = 1 ,12101.8 ,360.3,400,371.9
XS GIS Cut Line= 3
     2039793.895      215187.396     2040122.255      215068.947
     2040234.129      215099.285
#Sta/Elev= 30
       0 1757.78    39.2 1752.25    71.8  1743.8    87.31742.216   94.341741.988
   153.3 1739.29     186 1738.93   191.2 1737.85   195.7 1735.37   202.3    1734
   205.5 1734.22   218.6 1737.95     2221738.523   257.7 1737.33   287.1 1738.97
  296.491738.659   303.4 1737.18   319.7 1737.05     323 1737.55  333.891743.292
   349.1 1748.97   358.7 1751.81   387.7 1755.18   394.2  1756.9     407 1762.22
   419.9 1764.65   426.4 1767.53   432.8 1771.78   448.9 1777.92     465 1785.74
#Mann= 8 ,-1 , 0
       0     .12       0    87.3     .06       0   94.34     .12       0
   191.2    .045       0   218.6     .07       0     222     .12       0
  296.49    .016       0  333.89     .12       0
Bank Sta=191.2,218.6
XS Rating Curve= 0 ,0
Exp/Cntr=0.3,0.1

Type RM Length L Ch R = 1 ,11701.8 ,348,332,313
XS GIS Cut Line= 3
     2039936.822      215353.583     2040237.921      215330.618
     2040297.743      215298.713
#Sta/Elev= 30
       0 1759.53    42.2 1755.68    58.11753.584    87.7 1750.48   110.4 1748.97
   139.6 1748.26   181.8 1744.91   188.3 1743.82   204.6  1739.2   214.3 1738.07
   230.5 1737.64   239.6 1734.61     250 1733.56   256.5 1733.77   259.8  1734.8
   266.3    1738   269.5 1738.84   279.2  1739.2   282.5 1739.83   285.7 1742.45
     289 1746.33   292.2 1749.42  298.781754.052   311.7 1763.17   324.6 1773.59
   337.5 1782.17   350.4 1791.68   353.6 1793.36   363.3 1795.36   369.8  1800.2
#Mann= 5 ,-1 , 0
       0     .06       0    58.1     .12       0   239.6    .045       0
   259.8    .016       0  298.78     .12       0
Bank Sta=239.6,259.8
XS Rating Curve= 0 ,0
Exp/Cntr=0.3,0.1