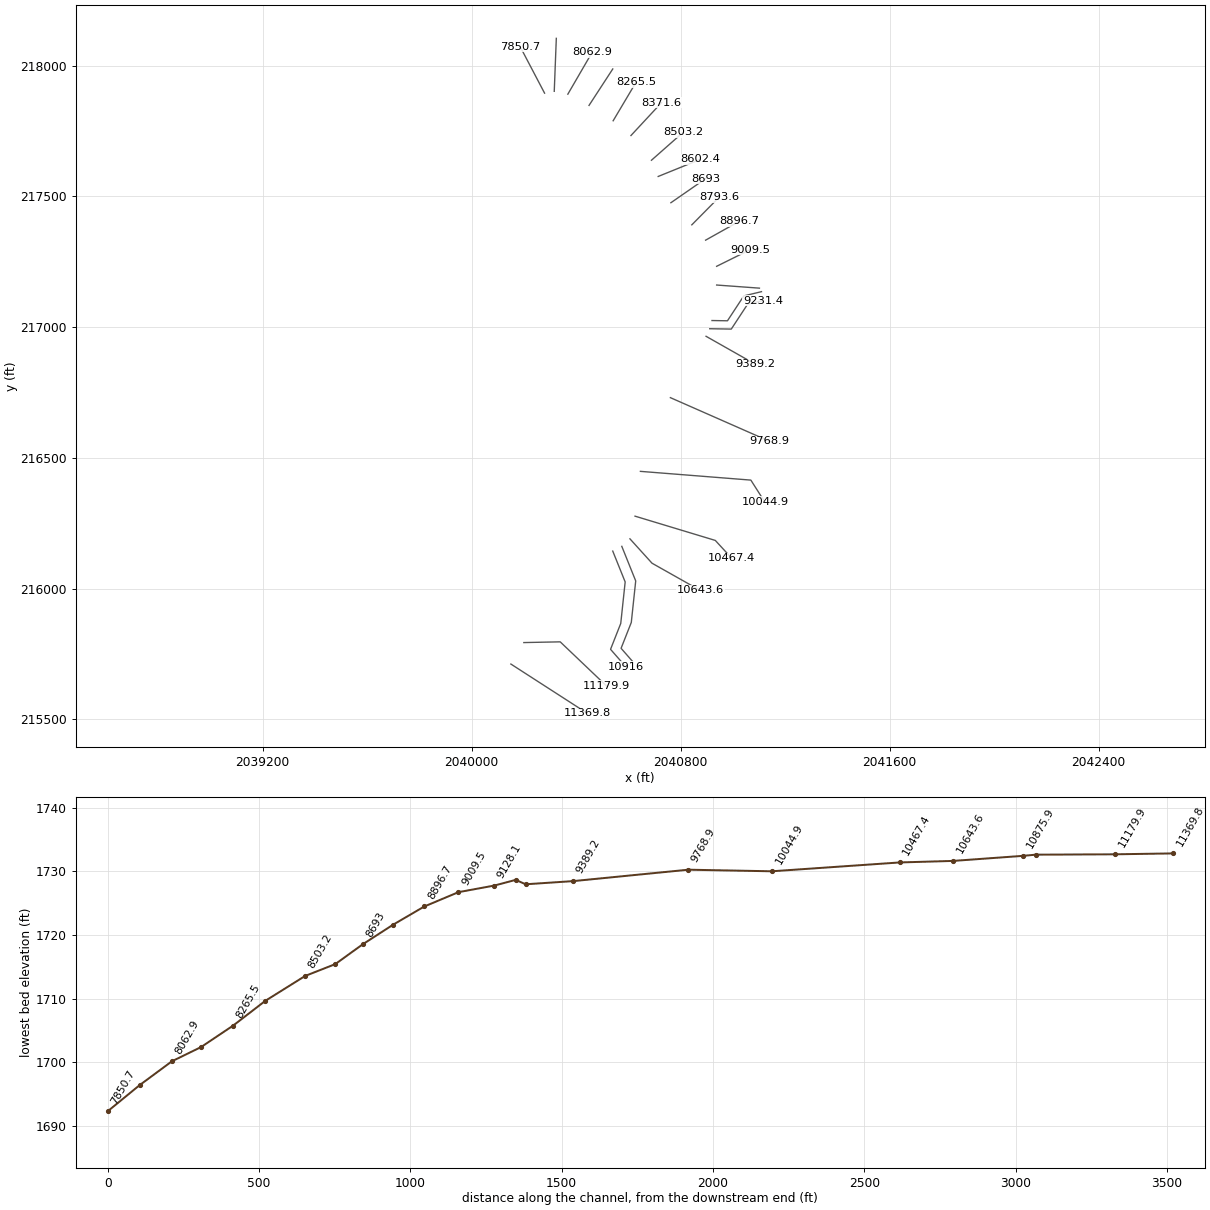
HEC-RAS study LTLSTNYCK.prj: LTLSTNYCK

--- LTLSTNYCK.g01 (geometry) --- (continued)

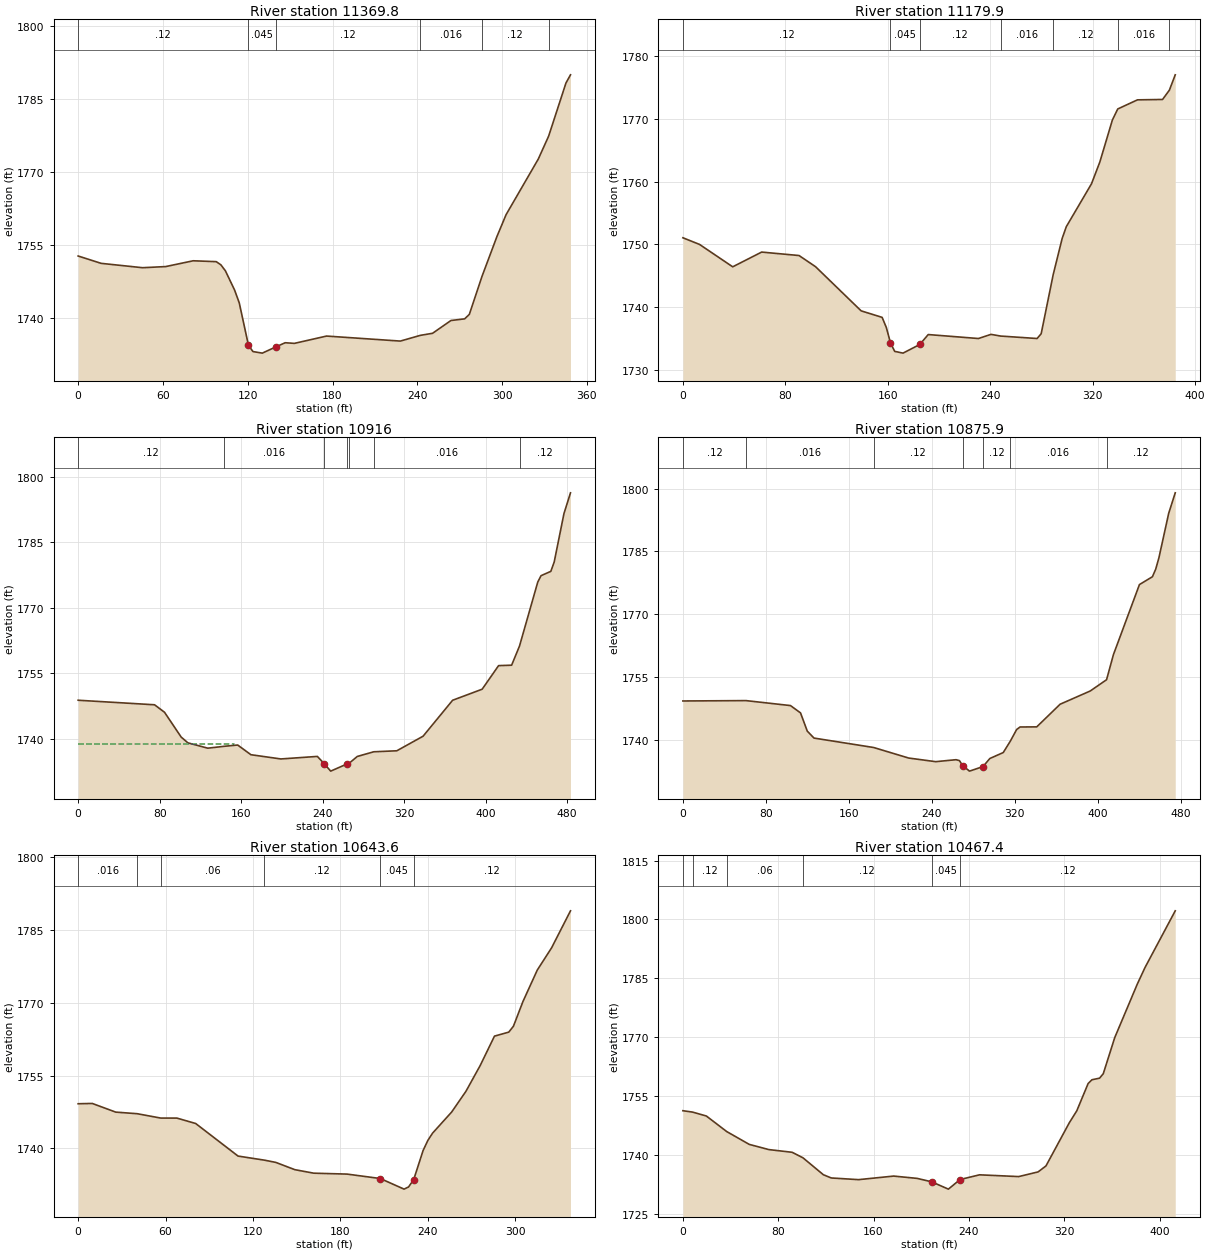
Type RM Length L Ch R = 1 ,11369.8 ,189.1,189.9,179.3
XS GIS Cut Line= 2
     2040150.117      215711.279     2040443.005      215522.529
#Sta/Elev= 30
       0 1752.74    16.3 1751.23    45.6 1750.34    61.9 1750.57    81.4 1751.76
    97.7 1751.58     101 1750.93   104.2  1749.7   110.7 1745.76     114 1743.13
   120.5 1734.44   123.7 1733.14   130.3 1732.82     140 1734.11   146.5 1734.95
     153 1734.82   175.8 1736.32     228 1735.29  242.111736.462   250.8 1736.89
   263.8 1739.51   273.5 1739.85   276.8 1740.76  285.731748.525   296.3  1756.7
   302.8 1761.21   325.6 1772.62  332.951777.339   345.2 1788.23   348.4  1789.9
#Mann= 6 ,-1 , 0
       0     .12       0   120.5    .045       0     140     .12       0
  242.11    .016       0  285.73     .12       0  332.95    .016       0
Bank Sta=120.5,140
XS Rating Curve= 0 ,0
Exp/Cntr=0.3,0.1

Type RM Length L Ch R = 1 ,11179.9 ,304.4,263.8,153.8
XS GIS Cut Line= 3
     2040199.845      215793.405     2040339.055      215796.189
     2040516.657      215627.103
#Sta/Elev= 30
       0 1751.07      13 1750.01    38.9 1746.44    61.5 1748.79    90.7 1748.24
   103.6 1746.46   139.2 1739.42   155.6 1738.38   158.9 1736.75   162.1 1734.32
   165.4 1732.96   171.9 1732.68     185 1734.06   191.6 1735.64   230.8 1735.01
   240.6 1735.67   248.11735.401   276.6 1735.01   279.8 1735.77  289.181745.189
   296.2 1750.97   299.4 1752.83   319.1 1759.68   325.6 1763.14   335.4 1769.84
  339.611771.608     355 1773.06   374.6 1773.12  379.941774.612   384.5 1777.05
#Mann= 7 ,-1 , 0
       0     .12       0   162.1    .045       0     185     .12       0
   248.1    .016       0  289.18     .12       0  339.61    .016       0
  379.94     .12       0
Bank Sta=162.1,185
XS Rating Curve= 0 ,0
Exp/Cntr=0.3,0.1

Type RM Length L Ch R = 1 ,10916   ,39.8,40.2,109.7
XS GIS Cut Line= 5
     2040540.213      216143.387     2040587.753      216025.356
     2040570.826      215866.502     2040531.764      215767.544
     2040591.054      215699.932
#Sta/Elev= 30
       0 1748.86      75 1747.82    84.8  1746.1   101.1 1740.43   107.7  1739.1
   127.2 1737.88  143.631738.312   156.6  1738.6   169.6 1736.38     199 1735.41
   234.8 1735.99   241.4 1734.36   247.9 1732.62   264.2 1734.29  265.911734.402
     274 1735.98  290.161737.051   312.8 1737.28   338.6 1740.62   367.6 1748.86
   396.6 1751.39   412.7 1756.79   425.5 1756.89  433.241761.272   451.2 1775.96
   454.4  1777.4     464 1778.39   467.3 1780.53   476.9 1791.64   483.3 1796.38
#Mann= 7 ,-1 , 0
       0     .12       0  143.63    .016       0   241.4    .045       0
   264.2    .016       0  265.91     .12       0  290.16    .016       0
  433.24     .12       0
#XS Ineff= 2 , 0
          153.22 1738.84
Permanent Ineff=
       F       F
Bank Sta=241.4,264.2
XS Rating Curve= 0 ,0
Exp/Cntr=0.3,0.1

Type RM Length L Ch R = 1 ,10875.9 ,188.1,232.2,280
XS GIS Cut Line= 5
     2040574.831      216161.561     2040628.118      216029.262
     2040611.191      215870.408     2040572.128       215771.45
     2040615.528      215721.959
#Sta/Elev= 30
       0 1749.21   60.811749.297   103.7 1748.11   113.4 1746.36   119.9    1742
   126.4 1740.34  183.851738.088   217.6 1735.57   243.7  1734.7   263.3 1735.17
   266.5 1734.96   269.8 1733.73   276.3 1732.44   289.3 1733.53   295.9 1735.46
   308.8 1736.88  315.561739.573   321.7 1742.38     325 1742.99   341.1 1743.02
   363.6 1748.43   392.6 1751.59   408.41754.289     415 1760.28   440.1 1777.04
   452.6 1778.91   455.8 1780.74   458.9 1783.48   468.3 1794.08   474.6 1798.97
#Mann= 7 ,-1 , 0
       0     .12       0   60.81    .016       0  183.85     .12       0
   269.8    .045       0   289.3     .12       0  315.56    .016       0
   408.4     .12       0
Bank Sta=269.8,289.3
XS Rating Curve= 0 ,0
Exp/Cntr=0.3,0.1

Type RM Length L Ch R = 1 ,10643.6 ,167.7,176.2,184.4
XS GIS Cut Line= 3
     2040606.072      216190.263     2040690.618      216096.971
     2040875.514      215992.804
#Sta/Elev= 30
       0  1749.2     9.7 1749.26    25.8 1747.48   40.531747.152   56.691746.255
    67.8 1746.25    80.7 1745.14   109.8 1738.44  127.911737.598   135.7 1737.14
   148.8 1735.64   161.8 1734.92   184.7 1734.73   207.5 1733.82   223.8 1731.64
   226.9 1732.09   230.4 1733.58   236.9  1739.6   240.2 1741.69   243.4 1743.16
   256.5  1747.5   266.3 1751.76   276.1 1757.07   285.9 1763.11   295.7 1763.93
   298.9 1765.14   305.5 1770.26   315.3  1776.7   325.1 1781.26   338.1 1788.88
#Mann= 6 ,-1 , 0
       0    .016       0   40.53     .12       0   56.69     .06       0
  127.91     .12       0   207.5    .045       0   230.4     .12       0
Bank Sta=207.5,230.4
XS Rating Curve= 0 ,0
Exp/Cntr=0.3,0.1

Type RM Length L Ch R = 1 ,10467.4 ,407.5,422.5,337.9
XS GIS Cut Line= 3
     2040625.453      216277.043     2040932.805       216184.21
     2040995.305      216116.502
#Sta/Elev= 30
       0 1751.35    8.18 1750.99    19.7    1750   36.771746.046    55.7 1742.78
    72.1 1741.46    91.7 1740.77  100.75 1739.37   117.9 1735.06   124.5 1734.24
   147.4 1733.81   176.9 1734.72   196.6 1734.13   208.7 1733.27   222.8  1731.4
   232.6 1733.84     249 1735.04   281.8 1734.59   298.1 1735.78   304.7  1737.3
   324.2 1748.23   330.6 1751.34   340.1 1758.27   343.3 1759.22   349.7 1759.63
   352.8 1760.76   362.4 1769.93   381.4 1783.59   387.8 1787.76   413.2  1802.2
#Mann= 6 ,-1 , 0
       0    .016       0    8.18     .12       0   36.77     .06       0
  100.75     .12       0   208.7    .045       0   232.6     .12       0
Bank Sta=208.7,232.6
XS Rating Curve= 0 ,0
Exp/Cntr=0.3,0.1

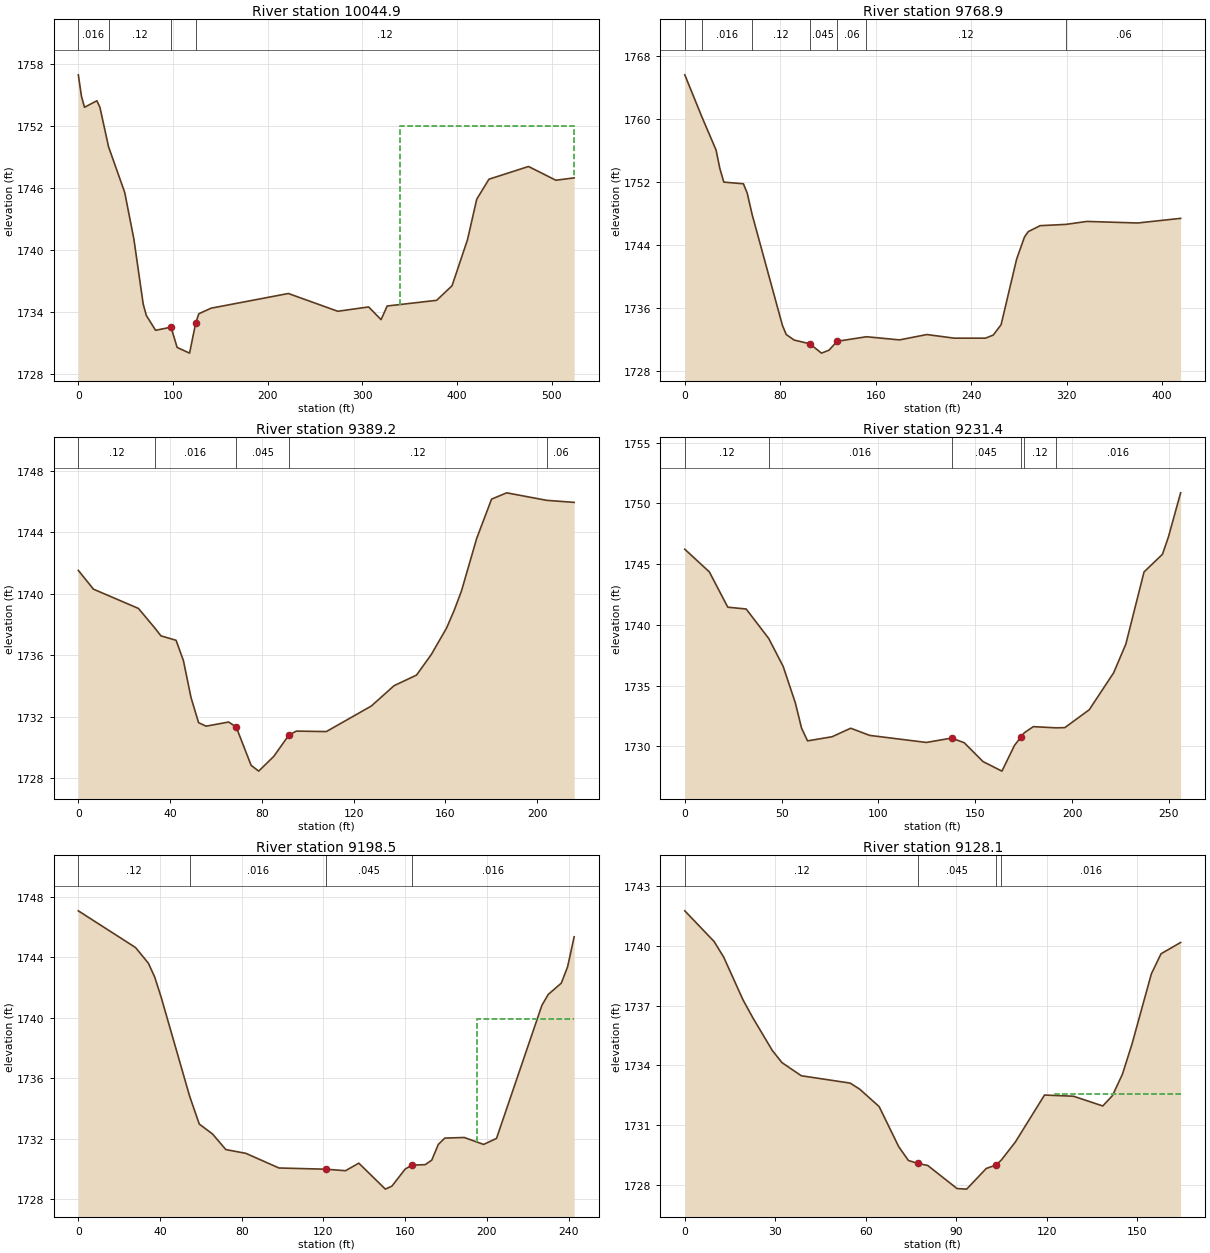
Type RM Length L Ch R = 1 ,10044.9 ,288.6,276,263.2
XS GIS Cut Line= 3
     2040646.044       216448.43     2041068.916      216414.983
     2041122.505      216331.027
#Sta/Elev= 30
       0 1756.94     3.3 1754.87     6.5  1753.8    19.6 1754.43    22.8  1753.8
   31.931749.982      49 1745.56    58.7 1741.04    68.5 1734.77    71.8 1733.66
    81.6 1732.22    97.9 1732.52   104.4 1730.56   117.5 1730.01     124 1732.92
   127.3 1733.82   140.3 1734.36   221.9 1735.78   274.1 1734.06   306.7 1734.48
   319.8 1733.25   326.3 1734.57   378.5 1735.12   394.8 1736.53   411.1 1740.98
   420.9 1744.91   433.8 1746.84   475.6 1748.07   504.5 1746.74   523.8 1746.97
#Mann= 4 ,-1 , 0
       0    .016       0   31.93     .12       0    97.9    .045       0
     124     .12       0
#XS Ineff= 2 , 0
                          339.72            1752
Permanent Ineff=
       F       F
Bank Sta=97.9,124
XS Rating Curve= 0 ,0
Exp/Cntr=0.3,0.1

Type RM Length L Ch R = 1 ,9768.9  ,376.7,379.7,372.2
XS GIS Cut Line= 2
     2040760.891      216730.412     2041141.139      216563.117
#Sta/Elev= 30
       0 1765.59   14.281760.266    26.2 1756.04    29.4 1753.68    32.7 1751.97
    49.1 1751.76    52.3 1750.57   56.461747.831    81.8 1733.78      85 1732.62
    91.6 1731.92   104.7 1731.45   114.5 1730.26   120.8 1730.63   127.6 1731.76
   152.21732.341   179.9 1731.94   202.8 1732.62   225.7 1732.16   251.9 1732.16
   258.4 1732.55     265 1733.87     278 1742.19   284.6 1745.01   287.8 1745.69
   297.7 1746.44  319.481746.606   336.9 1746.98   379.4 1746.78   415.4 1747.37
#Mann= 7 ,-1 , 0
       0     .12       0   14.28    .016       0   56.46     .12       0
   104.7    .045       0   127.6     .06       0   152.2     .12       0
  319.48     .06       0
Bank Sta=104.7,127.6
XS Rating Curve= 0 ,0
Exp/Cntr=0.3,0.1

Type RM Length L Ch R = 1 ,9389.2  ,61.2,157.8,210.8
XS GIS Cut Line= 2
      2040897.49      216965.121      2041085.54      216858.559
#Sta/Elev= 30
       0 1741.51     6.6 1740.29    26.2 1739.04   33.311737.773      36 1737.26
    42.6 1736.97    45.8 1735.65    49.1 1733.26    52.4 1731.62    55.7 1731.39
    65.5 1731.66    68.8 1731.34    75.3 1728.85    78.6 1728.47    85.2 1729.43
    91.7  1730.8      95 1731.07   108.1 1731.04   127.7  1732.7   137.6 1734.02
   147.4 1734.71   153.9 1736.06   160.5 1737.77   163.8 1738.91     167 1740.18
   173.6 1743.58   180.1 1746.14   186.7 1746.55  204.141746.062   216.1 1745.93
#Mann= 5 ,-1 , 0
       0     .12       0   33.31    .016       0    68.8    .045       0
    91.7     .12       0  204.14     .06       0
Bank Sta=68.8,91.7
XS Rating Curve= 0 ,0
Exp/Cntr=0.3,0.1

Type RM Length L Ch R = 1 ,9231.4  ,71.1,32.9,39.8
XS GIS Cut Line= 4
     2040911.538      216994.106     2040994.003      216992.717
     2041056.503      217087.856      2041114.64      217101.838
#Sta/Elev= 30
       0 1746.23    12.7 1744.36    22.2 1741.46    31.7 1741.31   43.351738.886
    50.8 1736.59    57.1 1733.59    60.3 1731.51    63.4 1730.46    76.1  1730.8
    85.7  1731.5    95.5 1730.91   124.8 1730.33   137.8 1730.69   144.3 1730.31
     154 1728.76   163.8 1727.97   170.3 1730.09   173.5 1730.75  175.341731.124
     180 1731.63  191.821731.533   196.3 1731.55   208.9 1733.02   221.5 1736.06
   227.8 1738.42   237.2 1744.36   246.7 1745.81   249.8 1747.24   256.1 1750.87
#Mann= 6 ,-1 , 0
       0     .12       0   43.35    .016       0   137.8    .045       0
   173.5    .016       0  175.34     .12       0  191.82    .016       0
Bank Sta=137.8,173.5
XS Rating Curve= 0 ,0
Exp/Cntr=0.3,0.1

Type RM Length L Ch R = 1 ,9198.5  ,112,70.5,26.1
XS GIS Cut Line= 4
     2040920.228      217025.485      2040979.42      217024.488
      2041041.92      217119.627      2041109.66      217135.919
#Sta/Elev= 30
       0 1747.09      28 1744.66    34.3 1743.62    37.4  1742.7    40.5 1741.39
    54.51734.807    59.2 1732.97    65.7 1732.31    72.2 1731.28      82 1731.03
    98.2 1730.06     121 1729.98   130.8 1729.88   137.3 1730.38   150.3 1728.66
   153.5 1728.86     160 1729.99   163.3 1730.25   169.8 1730.28     173 1730.58
   176.2 1731.62   179.4 1732.04   188.9 1732.08   198.4 1731.62   204.7 1732.02
   226.9 1740.83     230 1741.55   236.4  1742.3   239.5 1743.39   242.7 1745.37
#Mann= 4 ,-1 , 0
       0     .12       0    54.5    .016       0     121    .045       0
   163.3    .016       0
#XS Ineff= 2 , 0
                          195.15         1739.92
Permanent Ineff=
       F       F
Bank Sta=121,163.3
XS Rating Curve= 0 ,0
Exp/Cntr=0.3,0.1

Type RM Length L Ch R = 1 ,9128.1  ,98.3,118.6,138.4
XS GIS Cut Line= 2
      2040937.97      217161.294     2041101.816      217149.358
#Sta/Elev= 30
       0 1741.76     9.7 1740.22    12.9 1739.43    19.3 1737.28    22.6 1736.37
      29 1734.74    32.2 1734.13    38.6 1733.47    54.8  1733.1      58 1732.79
    64.4 1731.92    70.9  1729.9    74.1 1729.21    77.3 1729.06    80.5 1728.96
    90.2  1727.8    93.4 1727.77    99.9 1728.81   103.1 1728.98  104.831729.223
   109.5 1730.13   119.2  1732.5   128.8 1732.44   138.5 1731.95   141.7 1732.47
     145 1733.54   148.2 1735.07   154.6 1738.59   157.8  1739.6   164.3 1740.17
#Mann= 4 ,-1 , 0
       0     .12       0    77.3    .045       0   103.1     .12       0
  104.83    .016       0
#XS Ineff= 2 , 0
                          122.57         1732.55
Permanent Ineff=
       F       F
Bank Sta=77.3,103.1
XS Rating Curve= 0 ,0
Exp/Cntr=0.3,0.1

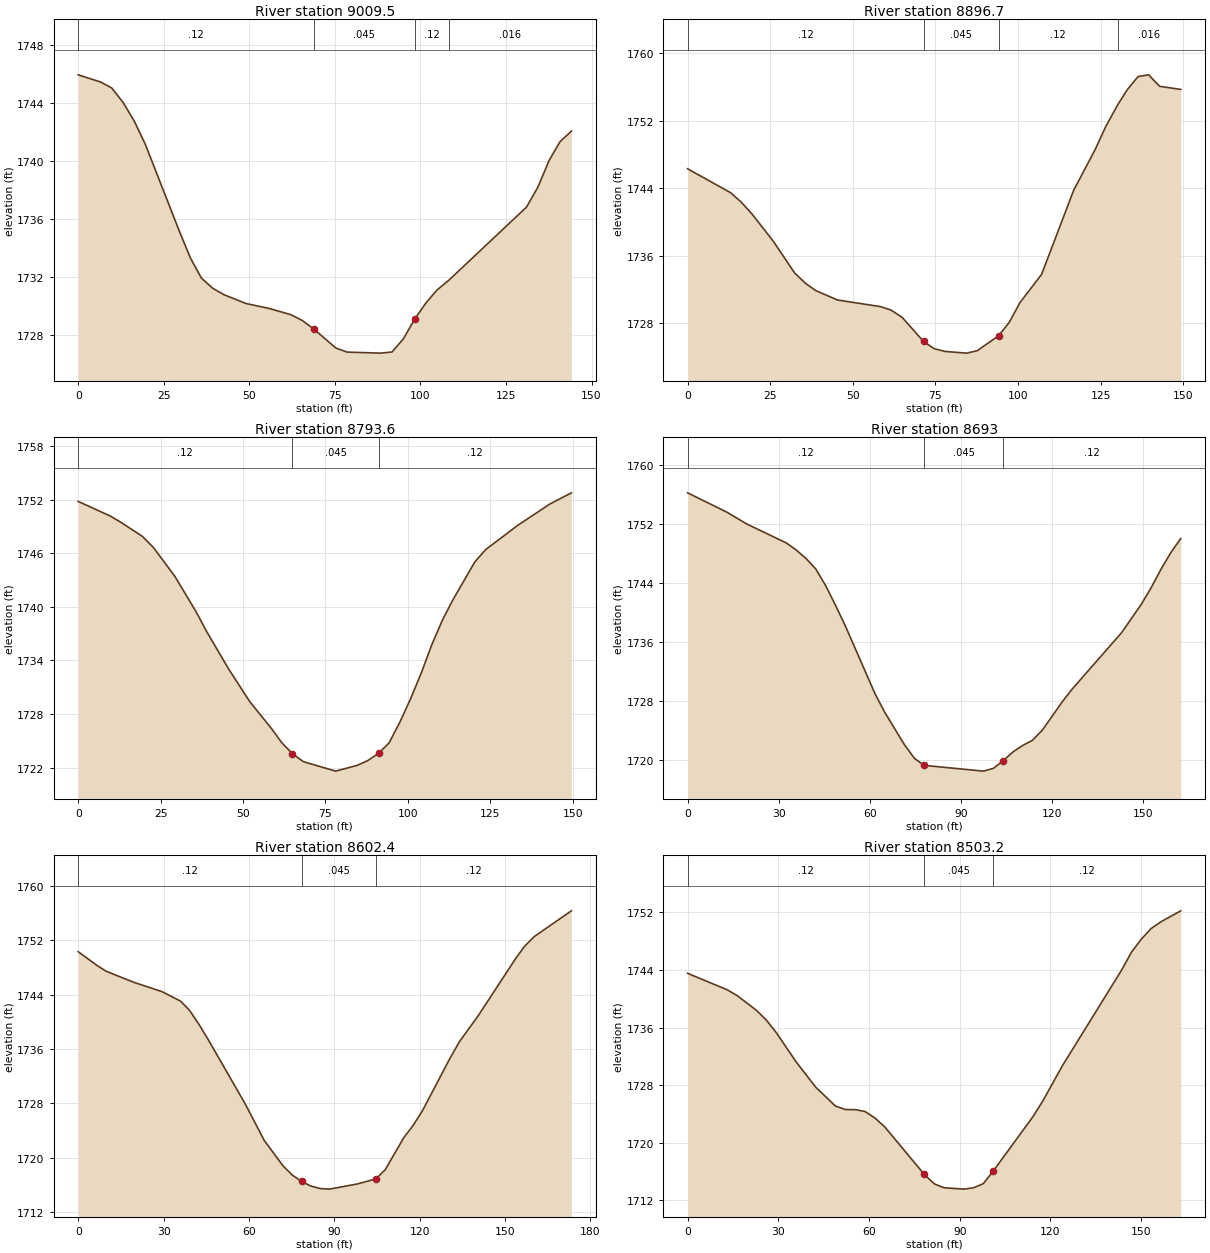
Type RM Length L Ch R = 1 ,9009.5  ,110.7,112.8,114.4
XS GIS Cut Line= 2
      2040937.97      217232.908     2041067.094      217296.927
#Sta/Elev= 30
       0 1745.94     6.6 1745.44     9.8 1745.03    13.1 1744.04    16.4 1742.74
    19.6 1741.15    29.5 1735.18    32.8 1733.29      36 1731.91    39.3 1731.21
    42.6 1730.76    49.1 1730.15    55.7 1729.82    62.2 1729.38    65.5 1728.98
    68.8  1728.4    75.3 1727.08    78.6  1726.8    88.4 1726.73    91.7 1726.81
      95 1727.71    98.3 1729.07   101.5 1730.16   104.8 1731.08  108.221731.745
     131 1736.81   134.3 1738.18   137.6 1740.03   140.8 1741.33   144.1 1742.05
#Mann= 4 ,-1 , 0
       0     .12       0    68.8    .045       0    98.3     .12       0
  108.22    .016       0
Bank Sta=68.8,98.3
XS Rating Curve= 0 ,0
Exp/Cntr=0.3,0.1

Type RM Length L Ch R = 1 ,8896.7  ,92.2,103.1,113.7
XS GIS Cut Line= 2
     2040895.739      217332.952     2041025.948      217405.868
#Sta/Elev= 30
       0 1746.32      13 1743.49    16.2 1742.38    19.5 1740.96      26  1737.7
    32.4 1733.97    35.7 1732.74    38.9 1731.86    45.4 1730.77    58.4 1729.99
    61.6 1729.57    64.9 1728.72    71.4 1725.86    74.6 1725.01    77.9 1724.68
    84.4 1724.48    87.6 1724.76    94.1 1726.54    97.3 1728.12   100.6 1730.49
   107.1 1733.81   116.8 1743.77   123.3 1748.59   126.5 1751.32  130.181753.935
     133 1755.68   136.3 1757.25   139.5 1757.45   142.8 1756.09   149.2 1755.72
#Mann= 4 ,-1 , 0
       0     .12       0    71.4    .045       0    94.1     .12       0
  130.18    .016       0
Bank Sta=71.4,94.1
XS Rating Curve= 0 ,0
Exp/Cntr=0.3,0.1

Type RM Length L Ch R = 1 ,8793.6  ,107.7,100.7,93.6
XS GIS Cut Line= 2
     2040842.918      217391.545      2040948.17      217497.882
#Sta/Elev= 30
       0  1751.8     9.8 1750.15      13 1749.45    19.5 1747.88    22.8 1746.65
    29.3 1743.43    35.8 1739.43      39 1737.22    45.5 1733.13      52 1729.42
    58.6  1726.4    61.8 1724.78      65 1723.57    68.3 1722.68    78.1 1721.62
    84.6 1722.26    87.8 1722.79    91.1 1723.61    94.3 1724.77    97.6 1727.12
   100.8 1729.69   104.1 1732.63   107.3  1735.8   110.6 1738.61   113.8 1740.87
   120.3 1745.02   123.6 1746.41   133.4 1749.14   143.1 1751.51   149.6 1752.76
#Mann= 3 ,-1 , 0
       0     .12       0      65    .045       0    91.1     .12       0
Bank Sta=65,91.1
XS Rating Curve= 0 ,0
Exp/Cntr=0.3,0.1

Type RM Length L Ch R = 1 ,8693    ,99,90.6,82.4
XS GIS Cut Line= 2
     2040762.848      217476.156     2040896.304      217568.629
#Sta/Elev= 30
       0 1756.19      13 1753.56    19.5 1751.97    32.5 1749.41    35.7 1748.48
      39 1747.31    42.2 1745.89    45.5 1743.61    48.7 1740.98      52 1738.13
    61.7 1729.02    64.9 1726.51    71.4 1722.11    74.7 1720.26    77.9 1719.31
    97.4 1718.53   100.7  1718.9   103.9 1719.94   107.2 1721.14   110.4 1722.02
   113.6 1722.71   116.9 1724.12   123.4 1727.92   126.6 1729.61   142.9 1737.26
   149.4  1741.1   152.6 1743.31   155.9 1745.85   159.1 1748.08   162.4    1750
#Mann= 3 ,-1 , 0
       0     .12       0    77.9    .045       0   103.9     .12       0
Bank Sta=77.9,103.9
XS Rating Curve= 0 ,0
Exp/Cntr=0.3,0.1

Type RM Length L Ch R = 1 ,8602.4  ,86.2,99.2,111.7
XS GIS Cut Line= 2
     2040714.229      217576.658     2040874.819      217641.762
#Sta/Elev= 30
       0  1750.3     6.5 1748.31     9.8 1747.43    19.6 1745.79    29.4 1744.44
      36 1743.03    39.2 1741.64    42.5 1739.58    45.8 1737.31    58.8 1727.85
    65.4 1722.56    71.9 1718.88    75.2 1717.49    78.5 1716.55    81.7 1715.88
      85 1715.51    88.3 1715.42    98.1 1716.18   104.6 1716.92   107.9 1718.28
   114.4 1722.97   117.7 1724.78     121 1726.96   130.8 1734.76     134  1737.1
   140.6 1740.91   153.7 1749.28   156.9 1751.11   160.2  1752.5   173.3  1756.3
#Mann= 3 ,-1 , 0
       0     .12       0    78.5    .045       0   104.6     .12       0
Bank Sta=78.5,104.6
XS Rating Curve= 0 ,0
Exp/Cntr=0.3,0.1

Type RM Length L Ch R = 1 ,8503.2  ,127.7,131.6,135.2
XS GIS Cut Line= 2
     2040688.404      217638.724     2040810.779       217746.58
#Sta/Elev= 30
       0 1743.55      13 1741.28    16.3 1740.48    22.8  1738.4    26.1 1737.03
    29.4 1735.27    35.9 1731.25    42.4 1727.72    48.9 1725.11    52.2 1724.63
    55.5 1724.61    58.7 1724.35      62 1723.44    65.2 1722.22    78.3 1715.61
    81.6  1714.3    84.8 1713.76    91.4 1713.57    94.6 1713.76    97.8 1714.33
   101.1 1716.09   114.2 1723.62   117.4 1725.76     124 1730.74   143.6 1744.04
   146.8 1746.48   150.1 1748.32   153.3 1749.77   156.6 1750.72   163.1 1752.23
#Mann= 3 ,-1 , 0
       0     .12       0    78.3    .045       0   101.1     .12       0
Bank Sta=78.3,101.1
XS Rating Curve= 0 ,0
Exp/Cntr=0.3,0.1

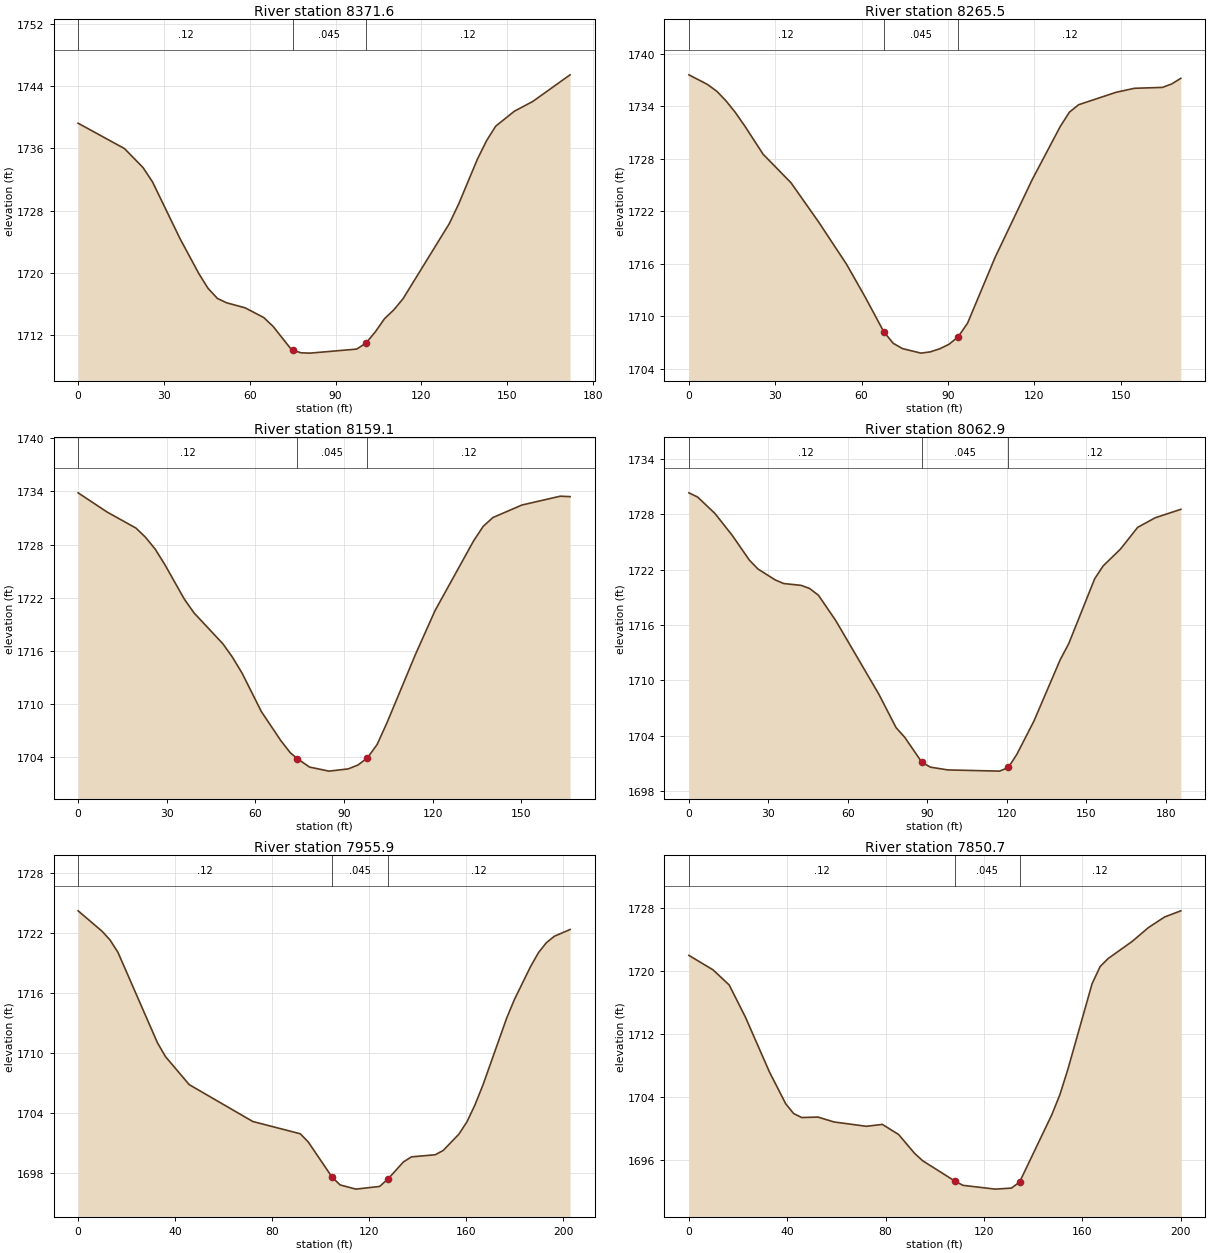
Type RM Length L Ch R = 1 ,8371.6  ,98.1,106.1,114
XS GIS Cut Line= 2
     2040609.943      217733.256     2040727.067      217859.238
#Sta/Elev= 30
       0 1739.25    16.2 1735.99    22.7 1733.54      26  1731.7    35.7 1724.34
    42.2  1719.9    45.4 1718.01    48.7  1716.7    51.9 1716.14    58.4 1715.49
    64.9 1714.24    68.2 1713.09    74.6 1710.11      75 1710.06    77.9  1709.7
    81.1 1709.66    97.4 1710.18   100.6 1710.94   103.9 1712.39   107.1 1714.08
   110.4 1715.24   113.6 1716.66   129.8 1726.34   133.1 1728.89   139.6 1734.62
   142.8    1737     146 1738.87   152.5 1740.79     159 1742.06     172 1745.48
#Mann= 3 ,-1 , 0
       0     .12       0      75    .045       0   100.6     .12       0
Bank Sta=75,100.6
XS Rating Curve= 0 ,0
Exp/Cntr=0.3,0.1

Type RM Length L Ch R = 1 ,8265.5  ,107.8,106.4,104.7
XS GIS Cut Line= 2
     2040541.805       217789.77      2040629.16      217936.684
#Sta/Elev= 30
       0 1737.62     6.4 1736.53     9.7 1735.74    12.9 1734.64    16.1 1733.33
    19.4 1731.77    25.8 1728.53    35.5 1725.26    45.2 1720.72    54.8 1715.93
    61.3 1712.16    67.7 1708.23      71  1706.9    74.2  1706.3    80.6 1705.78
    83.8 1705.92    87.1 1706.27    90.3 1706.78    93.5 1707.62    96.8  1709.2
   106.4 1716.75   119.3 1725.65     129  1731.7   132.2 1733.35   135.4  1734.2
   148.4 1735.62   154.8 1736.08   164.5 1736.18   167.7 1736.57   170.9 1737.22
#Mann= 3 ,-1 , 0
       0     .12       0    67.7    .045       0    93.5     .12       0
Bank Sta=67.7,93.5
XS Rating Curve= 0 ,0
Exp/Cntr=0.3,0.1

Type RM Length L Ch R = 1 ,8159.1  ,94.1,96.2,98
XS GIS Cut Line= 2
     2040449.368      217848.432     2040540.271        217987.9
#Sta/Elev= 30
       0 1733.84     9.8 1731.67    19.6 1729.85    22.8 1728.82    26.1 1727.47
    29.4  1725.7    35.9 1721.85    39.2 1720.28      49 1716.78    52.2 1715.28
    55.5 1713.46      62 1709.13    68.6 1705.84    71.8 1704.47    74.2  1703.8
    78.3 1702.85    84.9 1702.39    91.4 1702.64    94.7 1703.08    97.9 1703.88
   101.2  1705.4   104.5 1707.83   114.2  1715.6   120.8 1720.53   133.8 1728.38
   137.1 1730.05   140.4 1731.05   150.2 1732.46   163.2 1733.46   166.5 1733.41
#Mann= 3 ,-1 , 0
       0     .12       0    74.2    .045       0    97.9     .12       0
Bank Sta=74.2,97.9
XS Rating Curve= 0 ,0
Exp/Cntr=0.3,0.1

Type RM Length L Ch R = 1 ,8062.9  ,88.3,107,125.9
XS GIS Cut Line= 2
     2040368.309      217891.545     2040461.625      218052.136
#Sta/Elev= 30
       0 1730.35     3.3 1729.89     9.8 1728.12    16.3 1725.76    22.8 1723.06
    26.1 1722.08    32.6  1720.9    35.8 1720.51    42.4 1720.31    45.6 1719.97
    48.9 1719.24    55.4 1716.51    71.7 1708.51    78.2 1704.88    81.5 1703.82
      88  1701.1    91.2 1700.59    97.8 1700.29   117.3 1700.16   120.6 1700.56
   123.8 1701.98   130.3 1705.62   140.1  1712.2   143.4    1714   153.2 1721.04
   156.4 1722.43   162.9 1724.24   169.4  1726.6     176 1727.64   185.7 1728.56
#Mann= 3 ,-1 , 0
       0     .12       0      88    .045       0   120.6     .12       0
Bank Sta=88,120.6
XS Rating Curve= 0 ,0
Exp/Cntr=0.3,0.1

Type RM Length L Ch R = 1 ,7955.9  ,85.7,105.1,124.5
XS GIS Cut Line= 2
     2040316.225      217902.396     2040324.125      218105.087
#Sta/Elev= 30
       0 1724.26     9.8 1722.23    13.1 1721.36    16.4 1720.11    32.7 1711.05
      36 1709.67    45.8 1706.86      72 1703.17    91.6 1701.94    94.9 1701.11
   104.7  1697.6     108 1696.82   114.5  1696.4   124.3 1696.67   127.8 1697.43
   134.1 1699.12   137.4 1699.63   147.2 1699.84   150.5 1700.27     157 1701.91
   160.3 1703.14   163.6 1704.83   166.9 1706.83   176.7 1713.54   179.9  1715.4
   186.5 1718.67   189.8 1720.08     193 1721.06   196.3 1721.71   202.8 1722.39
#Mann= 3 ,-1 , 0
       0     .12       0   104.7    .045       0   127.8     .12       0
Bank Sta=104.7,127.8
XS Rating Curve= 0 ,0
Exp/Cntr=0.3,0.1

Type RM Length L Ch R = 1 ,7850.7  ,121.2,120.4,114.5
XS GIS Cut Line= 2
     2040279.125      217895.413     2040186.104      218072.535
#Sta/Elev= 30
       0 1721.96     9.8 1720.13    16.4  1718.2      23 1714.12    32.8 1707.15
    39.4 1703.13    42.6  1701.9    45.9 1701.39    52.5 1701.45      59 1700.83
    72.2 1700.28    78.7 1700.52    85.3 1699.24    91.8 1696.85    95.1 1695.91
   108.2 1693.33   111.5 1692.79   124.6 1692.31   131.2 1692.44   134.5  1693.2
   147.6 1701.73   150.9 1704.28   154.2 1707.55     164 1718.36   167.3 1720.55
   170.5 1721.55   180.4 1723.75   186.9 1725.48   193.5 1726.83   200.1 1727.61
#Mann= 3 ,-1 , 0
       0     .12       0   108.2    .045       0   134.5     .12       0
Bank Sta=108.2,134.5
XS Rating Curve= 0 ,0
Exp/Cntr=0.3,0.1