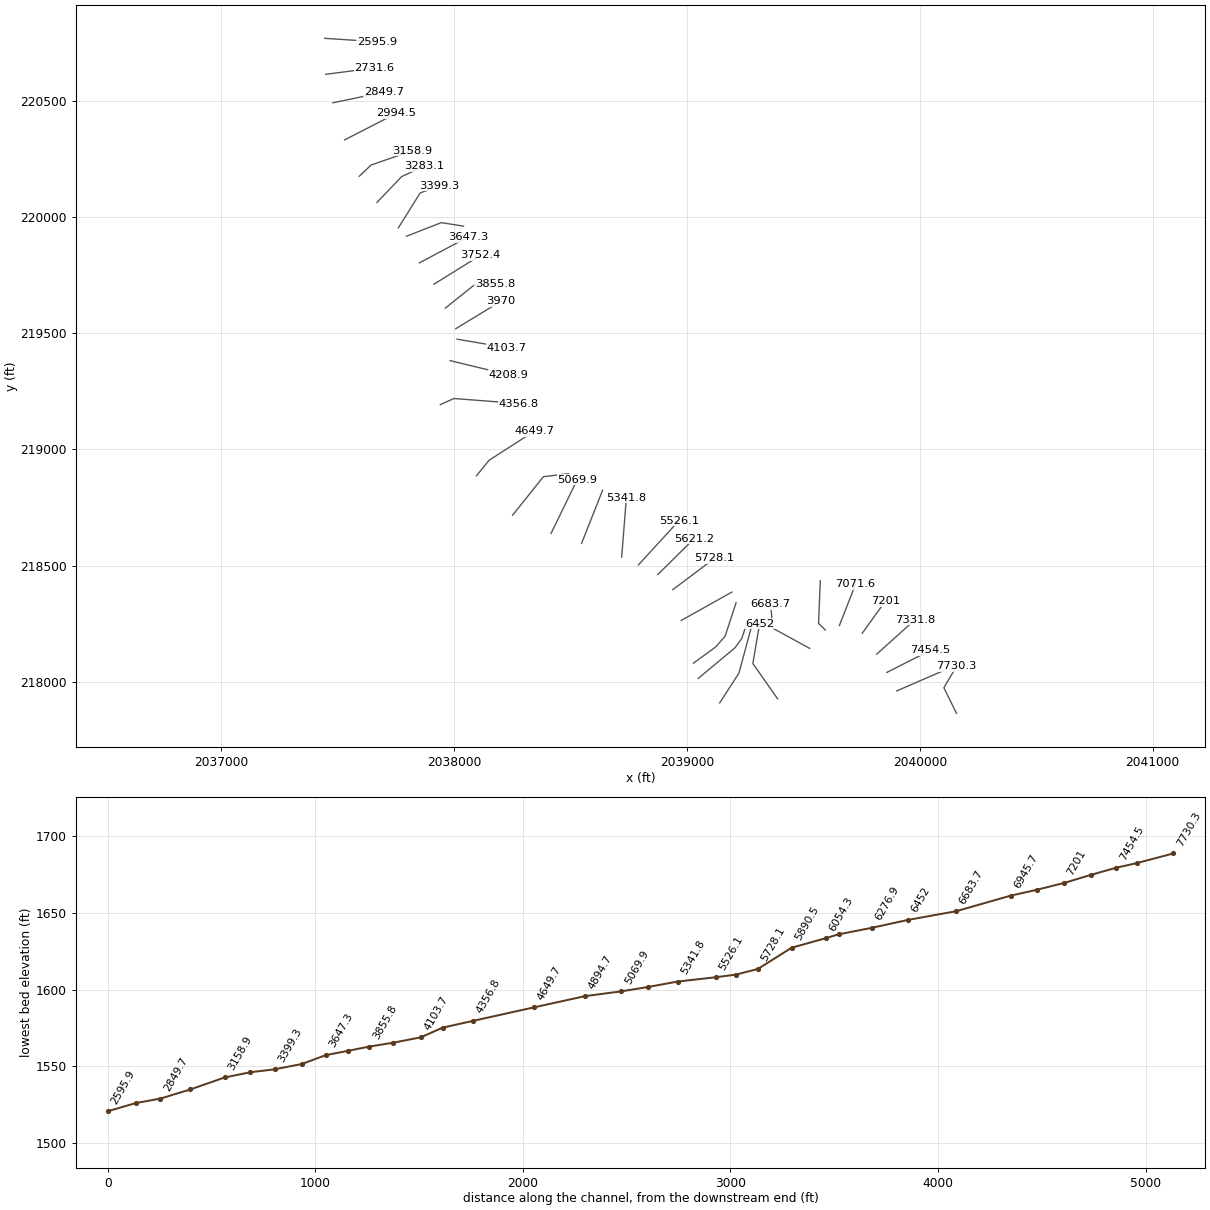
HEC-RAS study LTLSTNYCK.prj: LTLSTNYCK

--- LTLSTNYCK.g01 (geometry) --- (continued)

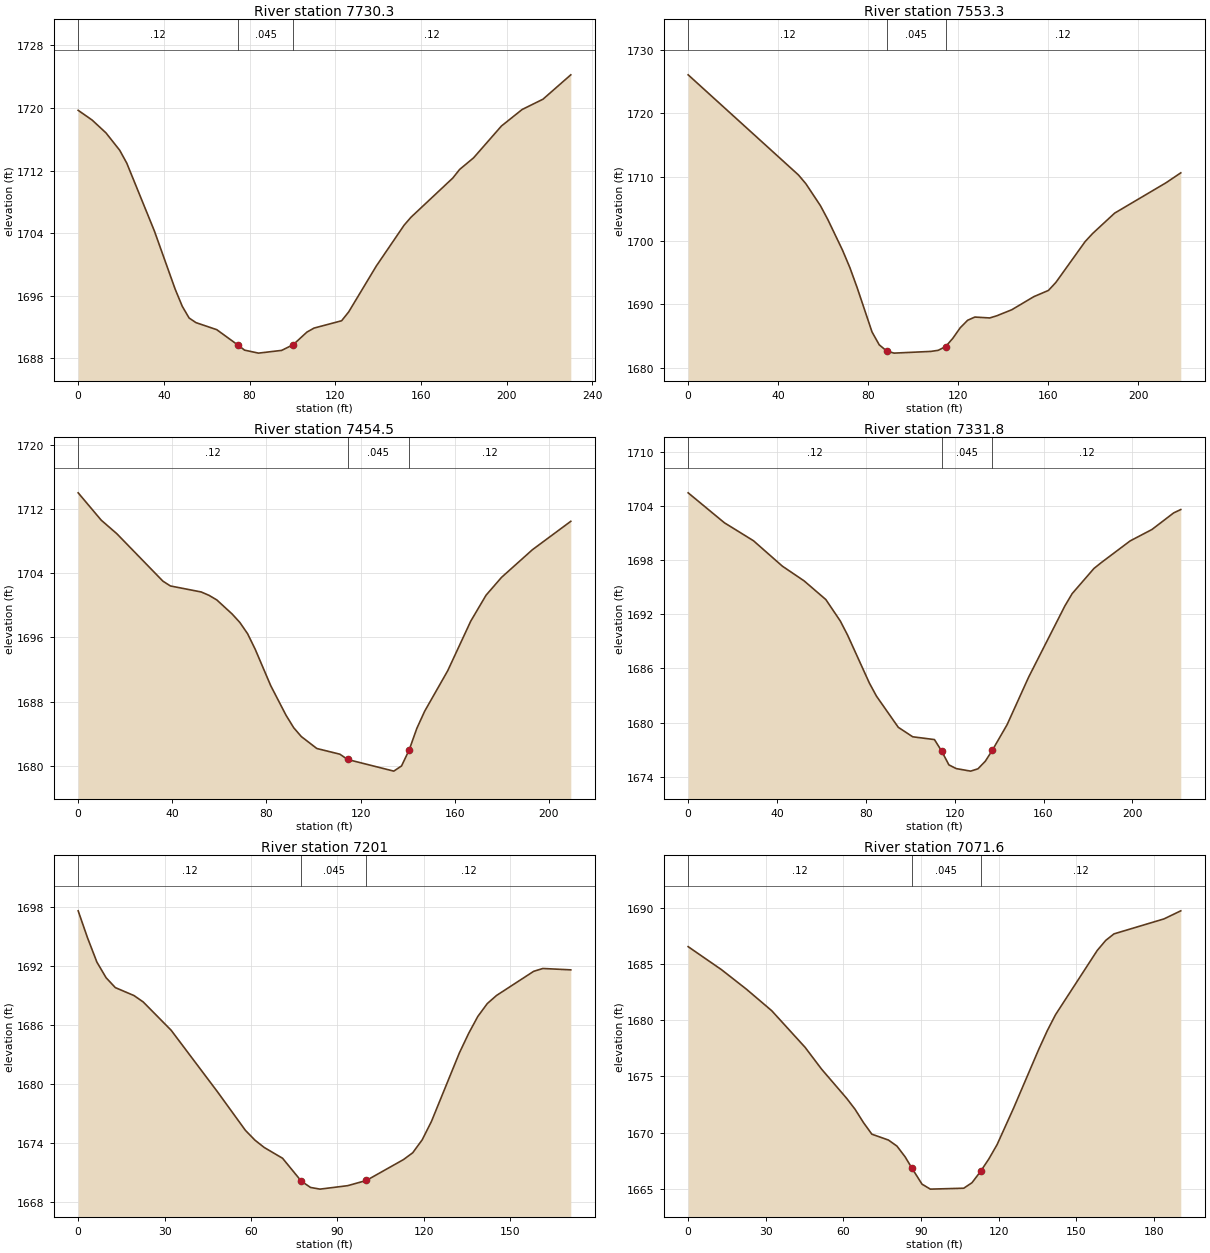
Type RM Length L Ch R = 1 ,7730.3  ,238.5,177,120.2
XS GIS Cut Line= 3
     2040157.863      217863.637     2040103.552      217974.011
     2040157.805      218066.242
#Sta/Elev= 30
       0  1719.7     6.5 1718.46      13 1716.81    19.4 1714.59    22.7 1712.94
    35.6 1704.26    45.3 1696.82    48.6 1694.64    51.8 1693.14      55 1692.55
    64.7 1691.65    74.5  1689.7    77.7 1689.03    84.2 1688.65      95    1689
   100.4 1689.73   106.8 1691.34   110.1 1691.85     123 1692.79   126.3 1693.92
   139.2 1699.79   152.2 1705.02   155.4 1706.03   174.9 1711.04   178.1 1712.14
   184.6 1713.62   197.6 1717.69   207.3 1719.81     217 1721.12     230 1724.24
#Mann= 3 ,-1 , 0
       0     .12       0    74.5    .045       0   100.4     .12       0
Bank Sta=74.5,100.4
XS Rating Curve= 0 ,0
Exp/Cntr=0.3,0.1

Type RM Length L Ch R = 1 ,7553.3  ,96.1,98.8,100.9
XS GIS Cut Line= 2
     2039901.708      217960.555     2040102.467      218047.795
#Sta/Elev= 30
       0 1726.08      49 1710.34    52.3 1708.96    58.8 1705.49    62.1  1703.3
    68.6  1698.5    71.9 1695.73    75.1 1692.61    81.7 1685.65    84.9 1683.63
    88.2 1682.66    91.5 1682.32   107.8 1682.59   111.1 1682.76   114.4 1683.34
   117.6 1684.65   120.9 1686.31   124.2 1687.49   127.4 1687.99     134 1687.85
   137.2  1688.2   143.8 1689.14   153.6  1691.2   160.1 1692.18   163.4 1693.44
   176.4 1699.86   179.7 1701.12   189.5 1704.33   212.4 1709.12   218.9 1710.67
#Mann= 3 ,-1 , 0
       0     .12       0    88.2    .045       0   114.4     .12       0
Bank Sta=88.2,114.4
XS Rating Curve= 0 ,0
Exp/Cntr=0.3,0.1

Type RM Length L Ch R = 1 ,7454.5  ,112.8,122.7,132.5
XS GIS Cut Line= 2
     2039858.369       218039.76     2040044.958      218134.601
#Sta/Elev= 30
       0 1714.02     9.8 1710.61    16.4 1708.93      36 1703.01    39.2 1702.41
    52.3 1701.66    55.6 1701.24    58.9 1700.67    65.4 1698.92    68.7 1697.86
      72 1696.45    75.2 1694.53    81.8 1689.99    88.3  1686.3    91.6 1684.73
    94.8 1683.64   101.4 1682.15   111.2 1681.44   114.5 1680.78   134.1 1679.33
   137.4 1679.98   140.6 1681.95   143.9 1684.67   147.2 1686.79     157 1691.84
   166.8 1698.03   173.3 1701.26   179.9 1703.49     193 1706.93   209.3 1710.47
#Mann= 3 ,-1 , 0
       0     .12       0   114.5    .045       0   140.6     .12       0
Bank Sta=114.5,140.6
XS Rating Curve= 0 ,0
Exp/Cntr=0.3,0.1

Type RM Length L Ch R = 1 ,7331.8  ,122.4,130.8,139.1
XS GIS Cut Line= 2
     2039815.112      218118.389     2039979.854      218266.979
#Sta/Elev= 30
       0 1705.43    16.3 1702.12    29.4 1700.13    42.4 1697.32    52.2 1695.69
      62 1693.62    68.5 1691.25    71.8 1689.68    81.6 1684.38    84.8 1682.93
    94.6 1679.49   101.1 1678.44   110.9 1678.13   114.2 1676.83   117.4 1675.33
   120.7 1674.92   127.2 1674.64   130.5  1674.9   133.8 1675.74     137 1676.97
   143.6 1679.78   153.3 1685.04   169.6 1692.91   172.9 1694.28   182.7 1697.06
     186 1697.71     199 1700.11   208.8 1701.37   218.6 1703.21   221.8 1703.58
#Mann= 3 ,-1 , 0
       0     .12       0   114.2    .045       0     137     .12       0
Bank Sta=114.2,137
XS Rating Curve= 0 ,0
Exp/Cntr=0.3,0.1

Type RM Length L Ch R = 1 ,7201    ,119.8,129.4,138.7
XS GIS Cut Line= 2
     2039752.965      218208.259     2039852.771      218347.275
#Sta/Elev= 30
       0 1697.57     3.2 1694.87     6.5 1692.37     9.7 1690.78    12.9 1689.78
    19.4 1688.97    22.6 1688.32    32.3 1685.45    48.4  1679.2    58.1 1675.29
    61.4  1674.3    64.6 1673.56      71 1672.46    77.5 1670.14    80.7  1669.5
      84 1669.33    93.6 1669.68   100.1 1670.21     113 1672.33   116.2 1673.02
   119.5 1674.34   122.7  1676.2   132.4 1683.15   135.6 1685.12   138.8 1686.85
   142.1 1688.16   145.3 1688.98   158.2 1691.43   161.4 1691.72   171.1 1691.58
#Mann= 3 ,-1 , 0
       0     .12       0    77.5    .045       0   100.1     .12       0
Bank Sta=77.5,100.1
XS Rating Curve= 0 ,0
Exp/Cntr=0.3,0.1

Type RM Length L Ch R = 1 ,7071.6  ,113.2,125.9,138.4
XS GIS Cut Line= 2
     2039654.951      218241.757     2039724.212      218419.106
#Sta/Elev= 30
       0 1686.55    12.9  1684.5    22.6 1682.75    32.3 1680.85    45.2 1677.59
    51.6 1675.64    61.3 1673.04    64.5 1672.08    67.8 1670.88      71 1669.86
    77.4 1669.34    80.7  1668.8    83.9 1667.83    86.5 1666.83    90.4 1665.41
    93.6 1664.97   106.5 1665.05   109.7 1665.54     113 1666.54   116.2 1667.65
   119.4 1668.93   125.8 1672.19   135.5 1677.41   138.8 1679.07     142  1680.5
   158.1 1686.21   161.4 1687.11   164.6 1687.69   183.9 1689.02   190.4 1689.74
#Mann= 3 ,-1 , 0
       0     .12       0    86.5    .045       0     113     .12       0
Bank Sta=86.5,113
XS Rating Curve= 0 ,0
Exp/Cntr=0.3,0.1

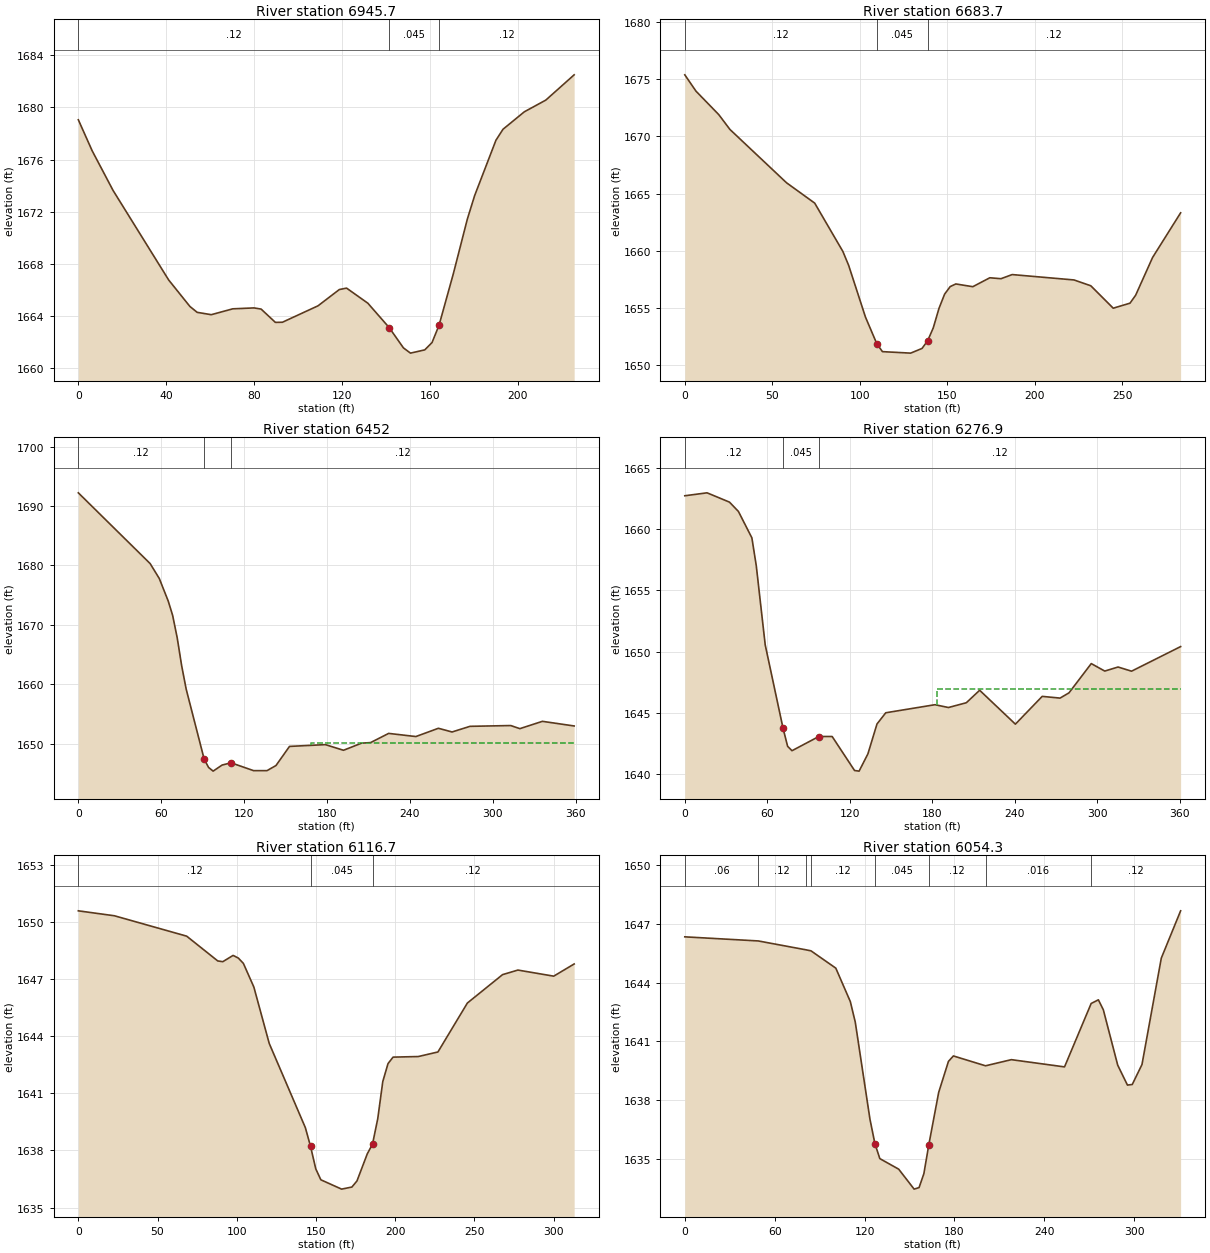
Type RM Length L Ch R = 1 ,6945.7  ,221.4,261.9,299.4
XS GIS Cut Line= 3
      2039594.92      218222.142     2039565.357      218250.703
     2039572.953      218435.165
#Sta/Elev= 30
       0 1679.05     6.3 1676.67    15.8 1673.63    41.1 1666.76    50.8 1664.72
    54.1 1664.27    60.5 1664.09    70.3 1664.54      80 1664.61    83.2 1664.52
    89.7  1663.5    92.9 1663.51   109.1 1664.77   118.8 1666.02   122.1 1666.13
   131.8 1664.97   141.5  1663.1     148 1661.54   151.2 1661.14   157.7 1661.39
     161 1661.95   164.2 1663.28   170.7 1667.23   177.1 1671.44   180.4 1673.23
   190.1 1677.48   193.3 1678.32     203 1679.66   212.8 1680.56   225.7  1682.5
#Mann= 3 ,-1 , 0
       0     .12       0   141.5    .045       0   164.2     .12       0
Bank Sta=141.5,164.2
XS Rating Curve= 0 ,0
Exp/Cntr=0.3,0.1

Type RM Length L Ch R = 1 ,6683.7  ,246.8,231.8,218.4
XS GIS Cut Line= 3
      2039527.38      218143.282      2039368.96      218230.087
     2039359.547      218332.184
#Sta/Elev= 30
       0 1675.39     6.4 1673.96    19.4 1671.91    25.8 1670.61    58.1 1665.95
    74.2 1664.17    90.3 1659.94    93.6 1658.72   103.2  1654.2   109.7 1651.86
   112.9 1651.18     129 1651.05   135.5 1651.46   138.7 1652.13   141.9 1653.25
   145.2 1654.97   148.4 1656.21   151.6 1656.87   154.8  1657.1   164.5 1656.86
   174.2 1657.64   180.6 1657.56     187 1657.92   222.3 1657.45   231.9 1656.94
   244.7 1654.98   254.3 1655.42   257.5 1656.11   267.2 1659.42   283.2 1663.32
#Mann= 3 ,-1 , 0
       0     .12       0   109.7    .045       0   138.7     .12       0
Bank Sta=109.7,138.7
XS Rating Curve= 0 ,0
Exp/Cntr=0.3,0.1

Type RM Length L Ch R = 1 ,6452    ,219.8,175,129.4
XS GIS Cut Line= 3
     2039389.576      217926.268     2039283.239      218078.177
     2039312.166      218249.276
#Sta/Elev= 30
       0 1692.22      52 1680.31    58.6 1677.81    65.1    1674    68.3 1671.58
    71.6 1667.81    74.8 1663.14    78.1 1659.17    91.1 1647.41    94.3    1646
    97.6 1645.38   104.1  1646.4   110.6 1646.78   126.9 1645.46   136.6 1645.46
   143.1 1646.32   152.9 1649.54   178.9 1649.84     192 1648.89   205.1 1650.09
   211.6 1650.18   224.7 1651.73   244.4  1651.2   260.7 1652.59   270.6 1651.97
   283.6 1652.92   313.1 1653.05   319.7 1652.53     336 1653.76     359 1652.98
#Mann= 3 ,-1 , 0
       0     .12       0    91.1    .045       0   110.6     .12       0
#XS Ineff= 2 , 0
                          168.47         1650.03
Permanent Ineff=
       F       F
Bank Sta=91.1,110.6
XS Rating Curve= 0 ,0
Exp/Cntr=0.3,0.1

Type RM Length L Ch R = 1 ,6276.9  ,164.2,160.2,148.4
XS GIS Cut Line= 3
     2039140.688      217908.626     2039223.561      218036.945
      2039277.54      218237.798
#Sta/Elev= 30
       0 1662.74    16.2 1662.98    32.5 1662.22      39 1661.46    48.8  1659.3
      52 1657.02    58.5 1650.55    71.5 1643.72    74.8 1642.26      78  1641.9
    97.5 1643.06   107.2 1643.06   123.5 1640.28   126.8 1640.23   133.2 1641.64
   139.8 1644.08   146.2    1645     182 1645.66   191.8 1645.43   204.8 1645.82
   214.5 1646.84   240.5 1644.07     260 1646.34     273  1646.2   279.5 1646.63
   295.7 1649.02   305.5 1648.41   315.2 1648.74     325  1648.4   360.7 1650.41
#Mann= 3 ,-1 , 0
       0     .12       0    71.5    .045       0    97.5     .12       0
#XS Ineff= 2 , 0
                          183.61         1646.98
Permanent Ineff=
       F       F
Bank Sta=71.5,97.5
XS Rating Curve= 0 ,0
Exp/Cntr=0.3,0.1

Type RM Length L Ch R = 1 ,6116.7  ,64.9,62.4,74
XS GIS Cut Line= 4
     2039048.529       218014.06     2039206.199      218145.452
     2039235.496      218185.599     2039253.592      218240.792
#Sta/Elev= 30
       0 1650.58    22.8 1650.32    68.4 1649.25      88 1647.95    91.2 1647.91
    97.7 1648.24     101  1648.1   104.2 1647.82   110.8 1646.58   120.5 1643.62
   143.3  1639.2   146.6 1638.21   149.9 1637.03   153.1 1636.46   166.2 1635.97
   172.7 1636.08   175.9  1636.4   182.4 1637.82   185.7 1638.33     189 1639.66
   192.2 1641.62   195.5 1642.56   198.7  1642.9   214.6 1642.93     227 1643.17
   245.6 1645.74   267.8 1647.23   277.5 1647.47   300.1 1647.15     313 1647.79
#Mann= 3 ,-1 , 0
       0     .12       0   146.6    .045       0   185.7     .12       0
Bank Sta=146.6,185.7
XS Rating Curve= 0 ,0
Exp/Cntr=0.3,0.1

Type RM Length L Ch R = 1 ,6054.3  ,175,163.8,148.3
XS GIS Cut Line= 4
     2039028.033       218079.82     2039122.649      218148.707
     2039163.882      218195.365     2039211.137      218339.494
#Sta/Elev= 30
       0 1646.35   49.04 1646.14   80.64 1645.69   84.251645.634   100.8 1644.75
   110.5 1643.04   113.8 1641.99   123.6 1637.03   126.9 1635.78   130.2 1635.01
   142.8 1634.47   153.1 1633.45   156.4 1633.53   159.6 1634.24   162.9 1635.72
   169.5  1638.4     176 1639.98   179.3 1640.26  200.761639.756     218 1640.07
   253.5  1639.7  271.291642.943   276.1 1643.13   279.4 1642.62     289 1639.79
   295.5 1638.77   298.7  1638.8   305.2 1639.82   318.1 1645.26     331 1647.68
#Mann= 8 ,-1 , 0
       0     .06       0   49.04     .12       0   80.64     .06       0
   84.25     .12       0   126.9    .045       0   162.9     .12       0
  200.76    .016       0  271.29     .12       0
Bank Sta=126.9,162.9
XS Rating Curve= 0 ,0
Exp/Cntr=0.3,0.1

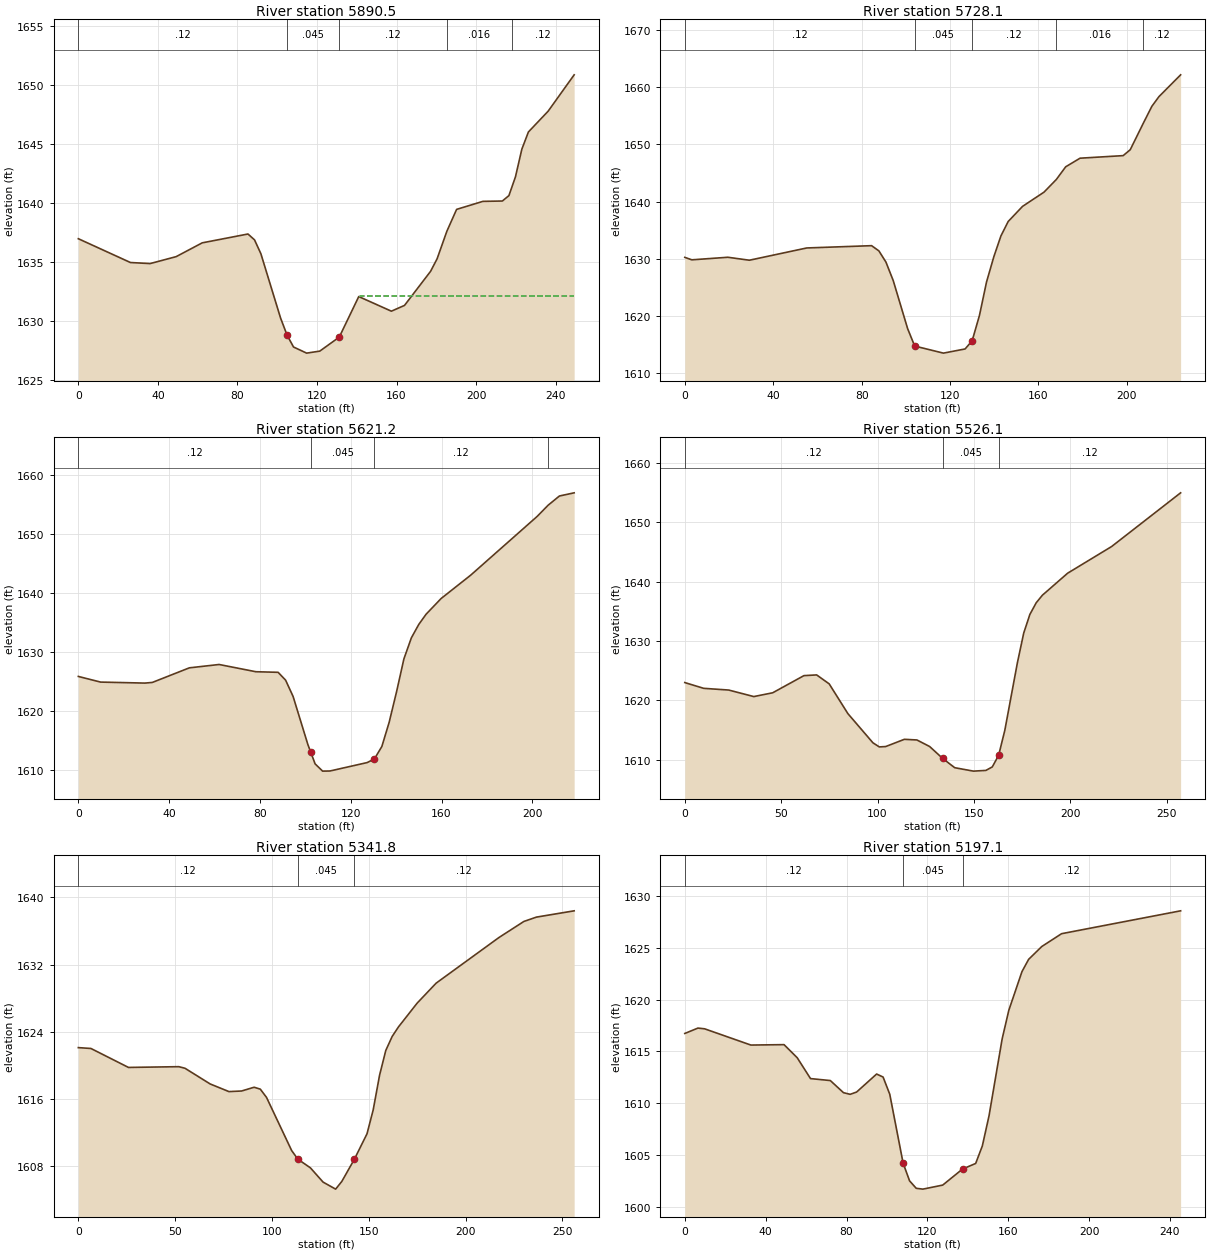
Type RM Length L Ch R = 1 ,5890.5  ,157.5,162.4,164.3
XS GIS Cut Line= 2
     2038975.696      218263.379      2039192.99      218385.559
#Sta/Elev= 30
       0 1636.97    26.2 1634.95    36.1 1634.86    49.2 1635.45    62.3 1636.62
    85.3 1637.37    88.6 1636.87    91.8 1635.69   101.7 1630.23     105 1628.77
   108.2 1627.78   114.8 1627.26   121.4 1627.43   131.2 1628.62     141 1632.06
   157.4 1630.82     164 1631.31   177.1  1634.2   180.4 1635.27  185.281637.596
   190.2 1639.46   203.4 1640.14   213.2 1640.17   216.5 1640.63  217.82 1641.27
   219.8 1642.23     223 1644.57   226.3 1646.03   236.2 1647.79   249.3 1650.88
#Mann= 5 ,-1 , 0
       0     .12       0     105    .045       0   131.2     .12       0
  185.28    .016       0  217.82     .12       0
#XS Ineff= 2 , 0
                          141.87         1632.12
Permanent Ineff=
       F       F
Bank Sta=105,131.2
XS Rating Curve= 0 ,0
Exp/Cntr=0.3,0.1

Type RM Length L Ch R = 1 ,5728.1  ,101.7,106.9,112.1
XS GIS Cut Line= 2
     2038939.288      218395.907     2039118.396      218530.868
#Sta/Elev= 30
       0 1630.21     3.2 1629.78    19.5 1630.23    29.2 1629.71    55.2 1631.86
    84.5 1632.26    87.8 1631.35      91 1629.38    94.3 1626.13   100.8 1617.73
     104 1614.67     117 1613.43   126.8 1614.16     130  1615.6   133.3 1620.04
   136.5  1625.9   139.8 1630.32     143 1633.96   146.3  1636.5   152.8 1639.15
   162.5 1641.64  168.081643.862   172.3 1646.08   178.8 1647.59   198.3 1648.04
   201.5 1649.07  207.421653.716   211.3 1656.69   214.5 1658.38   224.3  1662.2
#Mann= 5 ,-1 , 0
       0     .12       0     104    .045       0     130     .12       0
  168.08    .016       0  207.42     .12       0
Bank Sta=104,130
XS Rating Curve= 0 ,0
Exp/Cntr=0.3,0.1

Type RM Length L Ch R = 1 ,5621.2  ,93.3,95.1,96.9
XS GIS Cut Line= 2
     2038875.024      218460.892     2039029.984      218614.853
#Sta/Elev= 30
       0 1625.84     9.8 1624.88    29.3 1624.71    32.6 1624.82    48.9  1627.3
      62 1627.87    78.2 1626.64      88 1626.54    91.3 1625.21    94.6 1622.44
   101.1 1614.28   102.4 1612.94   104.3 1610.98   107.6 1609.75   110.8 1609.77
   127.2  1611.2   130.4 1611.81   133.7 1613.94   136.9 1618.03   140.2 1623.28
   143.4 1628.81   146.7  1632.4     150  1634.7   153.2 1636.42   159.8 1639.08
   172.8 1643.04   202.1 1653.03  206.931654.932   211.9  1656.5   218.4 1657.04
#Mann= 4 ,-1 , 0
       0     .12       0   102.4    .045       0   130.4     .12       0
  206.93    .016       0
Bank Sta=102.4,130.4
XS Rating Curve= 0 ,0
Exp/Cntr=0.3,0.1

Type RM Length L Ch R = 1 ,5526.1  ,158.5,184.3,210
XS GIS Cut Line= 2
     2038791.875      218502.467     2038965.314      218692.327
#Sta/Elev= 30
       0    1623     9.8 1622.03    22.8 1621.74    35.8 1620.64    45.6 1621.28
    61.8 1624.17    68.4 1624.29    74.9 1622.78    84.6 1617.77    97.6 1612.85
   100.9 1612.16   104.2 1612.22   113.9 1613.44   120.4 1613.33     127 1612.23
   133.7 1610.24     140 1608.66   149.7 1608.08   156.2  1608.2   159.5 1608.79
   162.8 1610.74     166 1614.95   172.5 1626.29   175.8 1631.33     179 1634.48
   182.3 1636.45   185.5 1637.72   198.6 1641.43   221.4 1645.92   257.2 1654.97
#Mann= 3 ,-1 , 0
       0     .12       0   133.7    .045       0   162.8     .12       0
Bank Sta=133.7,162.8
XS Rating Curve= 0 ,0
Exp/Cntr=0.3,0.1

Type RM Length L Ch R = 1 ,5341.8  ,155.8,144.7,133.6
XS GIS Cut Line= 2
     2038719.953       218536.17     2038740.106       218791.44
#Sta/Elev= 30
       0 1622.11     6.5 1622.01    25.9 1619.75    51.9 1619.84    55.1 1619.65
    68.1 1617.78    77.8 1616.87    84.3 1616.94    90.8 1617.39      94 1617.16
    97.2 1616.18   110.2 1609.84   113.4 1608.82   119.9 1607.78   126.4 1606.09
   132.9 1605.25   136.1 1606.17   142.6 1608.82   149.1 1611.84   152.3 1614.69
   155.6 1618.83   158.8 1621.77   162.1 1623.44   165.3 1624.56     175 1627.41
   184.8 1629.79   217.2 1635.22   230.1 1637.14   236.6 1637.66   256.1 1638.41
#Mann= 3 ,-1 , 0
       0     .12       0   113.4    .045       0   142.6     .12       0
Bank Sta=113.4,142.6
XS Rating Curve= 0 ,0
Exp/Cntr=0.3,0.1

Type RM Length L Ch R = 1 ,5197.1  ,130,127.1,124.3
XS GIS Cut Line= 2
     2038547.878      218595.631     2038637.927      218823.837
#Sta/Elev= 30
       0 1616.72     6.5 1617.24     9.8 1617.17    32.7  1615.6    49.1 1615.64
    55.6 1614.38    62.2 1612.36      72 1612.17    78.5    1611    81.8 1610.84
      85 1611.06    94.9  1612.8    98.1 1612.51   101.4 1610.85     108  1604.2
   111.2 1602.48   114.5 1601.76   117.8 1601.68   127.6 1602.07   137.4 1603.62
   143.9 1604.16   147.2 1605.85   150.5 1608.75     157 1616.19   160.3 1618.96
   166.8 1622.69   170.1 1623.88   176.6 1625.12   186.4 1626.36   245.3 1628.57
#Mann= 3 ,-1 , 0
       0     .12       0     108    .045       0   137.4     .12       0
Bank Sta=108,137.4
XS Rating Curve= 0 ,0
Exp/Cntr=0.3,0.1

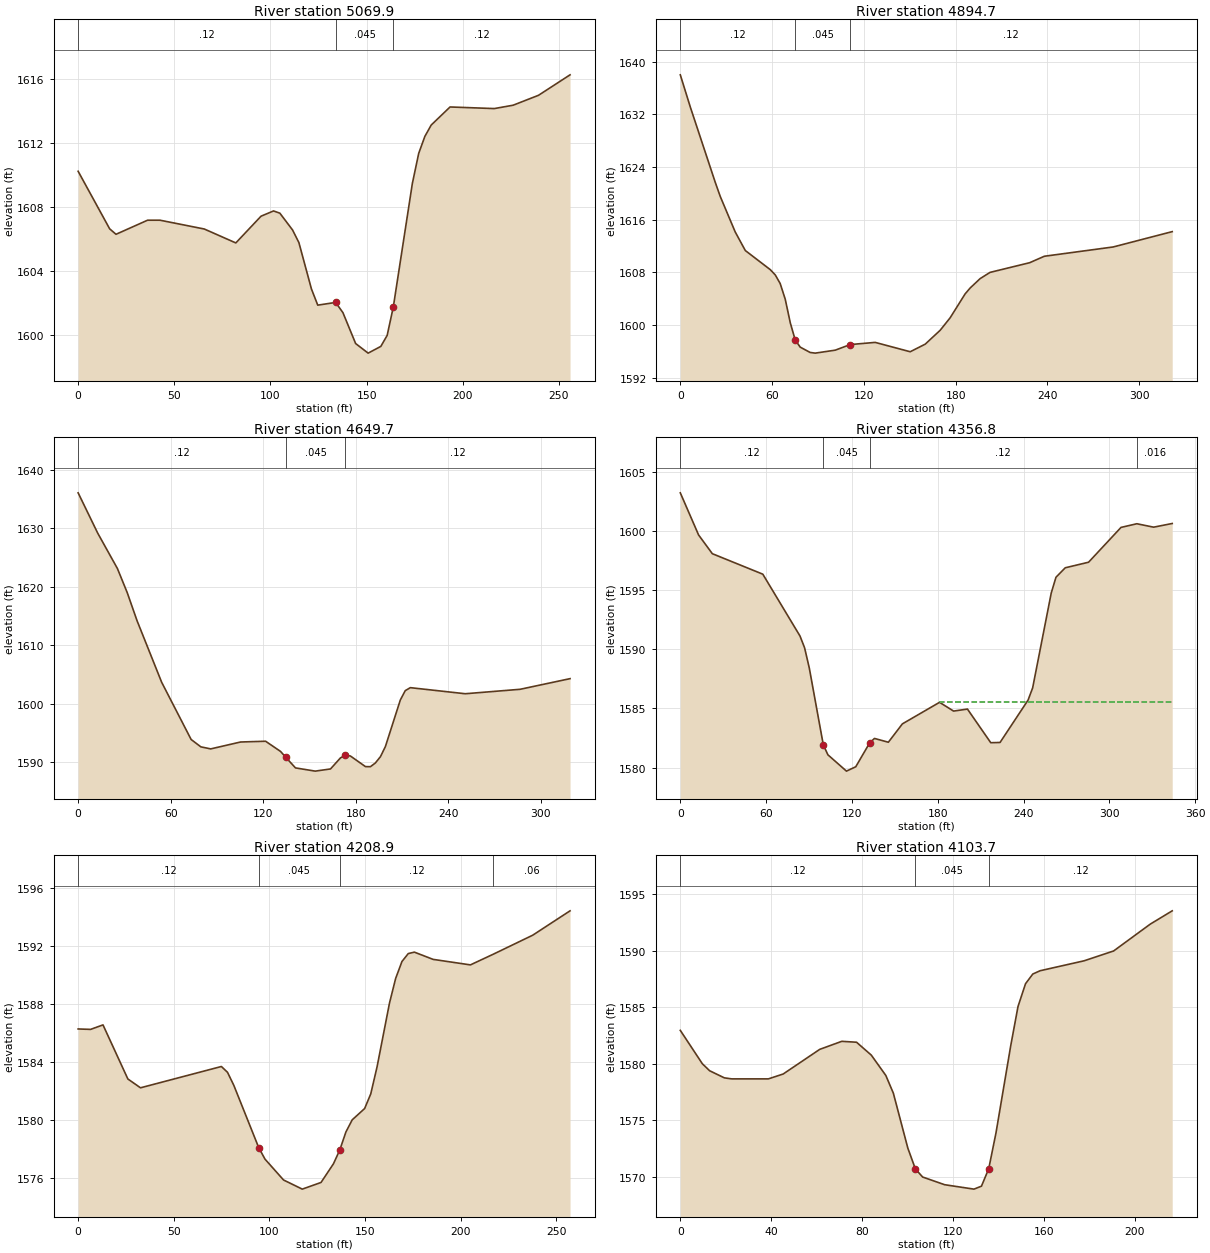
Type RM Length L Ch R = 1 ,5069.9  ,184.5,175.2,165.3
XS GIS Cut Line= 2
     2038416.703       218638.29     2038528.465      218868.325
#Sta/Elev= 30
       0 1610.25    16.4 1606.65    19.7 1606.31    36.1 1607.19    42.6 1607.19
    65.6 1606.64      82 1605.77    95.1 1607.44   101.6 1607.77   104.9 1607.63
   111.5 1606.58   114.8 1605.79   121.3  1602.9   124.6 1601.88   133.9 1602.05
   137.7 1601.41   144.3 1599.48   150.8 1598.88   157.4  1599.3   160.7 1599.99
   163.9 1601.77   173.8 1609.49   177.1 1611.37   180.3 1612.43   183.6 1613.14
   193.4 1614.27   216.4 1614.17   226.2 1614.38   239.4    1615   255.8 1616.28
#Mann= 3 ,-1 , 0
       0     .12       0   133.9    .045       0   163.9     .12       0
Bank Sta=133.9,163.9
XS Rating Curve= 0 ,0
Exp/Cntr=0.3,0.1

Type RM Length L Ch R = 1 ,4894.7  ,254.8,245,234.1
XS GIS Cut Line= 3
     2038251.338      218716.198     2038383.717      218882.214
     2038492.224      218895.235
#Sta/Elev= 30
       0 1638.01     6.5 1633.15    22.9 1621.65    26.1 1619.55    35.9 1614.15
    42.5 1611.33    58.8 1608.43    62.1 1607.62    65.3 1606.32    68.6 1603.94
    71.9 1600.36    75.1 1597.76    78.4 1596.66    84.9 1595.85    88.2 1595.75
   101.3  1596.2   111.1 1597.05   127.4 1597.38   150.3 1595.96   160.1 1597.11
   169.9 1599.22   176.4 1601.11   186.2 1604.74   189.5 1605.64     196 1607.06
   202.5 1608.01   228.4 1609.48     238 1610.46     283 1611.87   321.6  1614.2
#Mann= 3 ,-1 , 0
       0     .12       0    75.1    .045       0   111.1     .12       0
Bank Sta=75.1,111.1
XS Rating Curve= 0 ,0
Exp/Cntr=0.3,0.1

Type RM Length L Ch R = 1 ,4649.7  ,319.5,292.9,267
XS GIS Cut Line= 3
     2038096.229      218885.964     2038150.427      218952.743
      2038346.32       219079.03
#Sta/Elev= 30
       0 1636.05    12.7 1629.16    25.5  1623.1    31.8 1619.02    38.2  1614.2
    54.2 1603.65    73.3 1593.88    79.6 1592.62      86 1592.27   105.4 1593.45
   121.6 1593.58   131.3 1591.84   134.6 1590.86     141 1589.02   153.8 1588.47
   163.7 1588.84   170.2 1590.74   173.4 1591.19   176.6 1591.06   186.4 1589.24
   189.6 1589.23   192.8 1589.86   196.1 1590.94   199.3 1592.66     209 1600.63
   212.2 1602.23   215.5 1602.74   251.1  1601.7   286.7 1602.46   319.1 1604.28
#Mann= 3 ,-1 , 0
       0     .12       0   134.6    .045       0   173.4     .12       0
Bank Sta=134.6,173.4
XS Rating Curve= 0 ,0
Exp/Cntr=0.3,0.1

Type RM Length L Ch R = 1 ,4356.8  ,153.8,147.9,141.7
XS GIS Cut Line= 3
     2037941.007      219192.472     2037999.602      219218.585
     2038278.666       219197.04
#Sta/Elev= 30
       0  1603.2    12.8 1599.64    22.4 1598.06    57.7 1596.33    83.7 1591.11
    86.9 1590.12    90.2 1588.41     100 1581.92   103.2 1581.08   116.2  1579.7
   122.7 1580.07   132.5  1582.1   135.8 1582.46   145.5 1582.14   155.3 1583.69
   181.3 1585.51   191.1 1584.77   200.8 1584.94   217.1  1582.1   223.6 1582.12
   243.2  1585.7   246.4 1586.73   259.4 1594.74   262.7 1596.07   269.2 1596.87
   285.5 1597.34   308.2 1600.28  319.271600.589     331  1600.3     344 1600.61
#Mann= 4 ,-1 , 0
       0     .12       0     100    .045       0   132.5     .12       0
  319.27    .016       0
#XS Ineff= 2 , 0
                          181.84         1585.56
Permanent Ineff=
       F       F
Bank Sta=100,132.5
XS Rating Curve= 0 ,0
Exp/Cntr=0.3,0.1

Type RM Length L Ch R = 1 ,4208.9  ,102.2,105.2,107.4
XS GIS Cut Line= 2
     2037983.323        219381.5     2038233.326      219321.016
#Sta/Elev= 30
       0  1586.3     6.5 1586.27      13 1586.58      26 1582.85    32.6 1582.24
    74.9 1583.71    78.1 1583.31    81.4 1582.41    94.4 1578.12    97.7 1577.32
   107.4 1575.88   117.2 1575.25     127 1575.71   133.5    1577   136.8 1577.95
     140 1579.19   143.3 1580.03   149.8 1580.81     153 1581.82   156.3 1583.69
   162.8 1588.09     166 1589.78   169.3 1590.95   172.6  1591.5   175.8  1591.6
   185.6  1591.1   205.1 1590.72  217.12 1591.46   237.7 1592.77   257.2 1594.45
#Mann= 4 ,-1 , 0
       0     .12       0    94.4    .045       0   136.8     .12       0
  217.12     .06       0
Bank Sta=94.4,136.8
XS Rating Curve= 0 ,0
Exp/Cntr=0.3,0.1

Type RM Length L Ch R = 1 ,4103.7  ,106.8,133.8,160.9
XS GIS Cut Line= 2
      2038012.84      219474.011     2038226.382      219437.552
#Sta/Elev= 30
       0 1582.97     9.7 1580.02    12.9  1579.4    19.4 1578.77    22.6 1578.68
    38.8 1578.68    45.3 1579.11    61.4 1581.29    71.1    1582    77.6 1581.92
    84.1 1580.78    90.5 1578.98    93.8 1577.42   100.2 1572.55   103.5 1570.72
   106.7    1570   116.4 1569.32   129.3 1568.93   132.6 1569.19   135.8 1570.73
     139  1573.9   145.5 1581.62   148.7 1585.08     152 1587.09   155.2 1587.95
   158.4 1588.24   177.8 1589.12   190.8 1589.99   206.9 1592.36   216.6 1593.54
#Mann= 3 ,-1 , 0
       0     .12       0   103.5    .045       0   135.8     .12       0
Bank Sta=103.5,135.8
XS Rating Curve= 0 ,0
Exp/Cntr=0.3,0.1

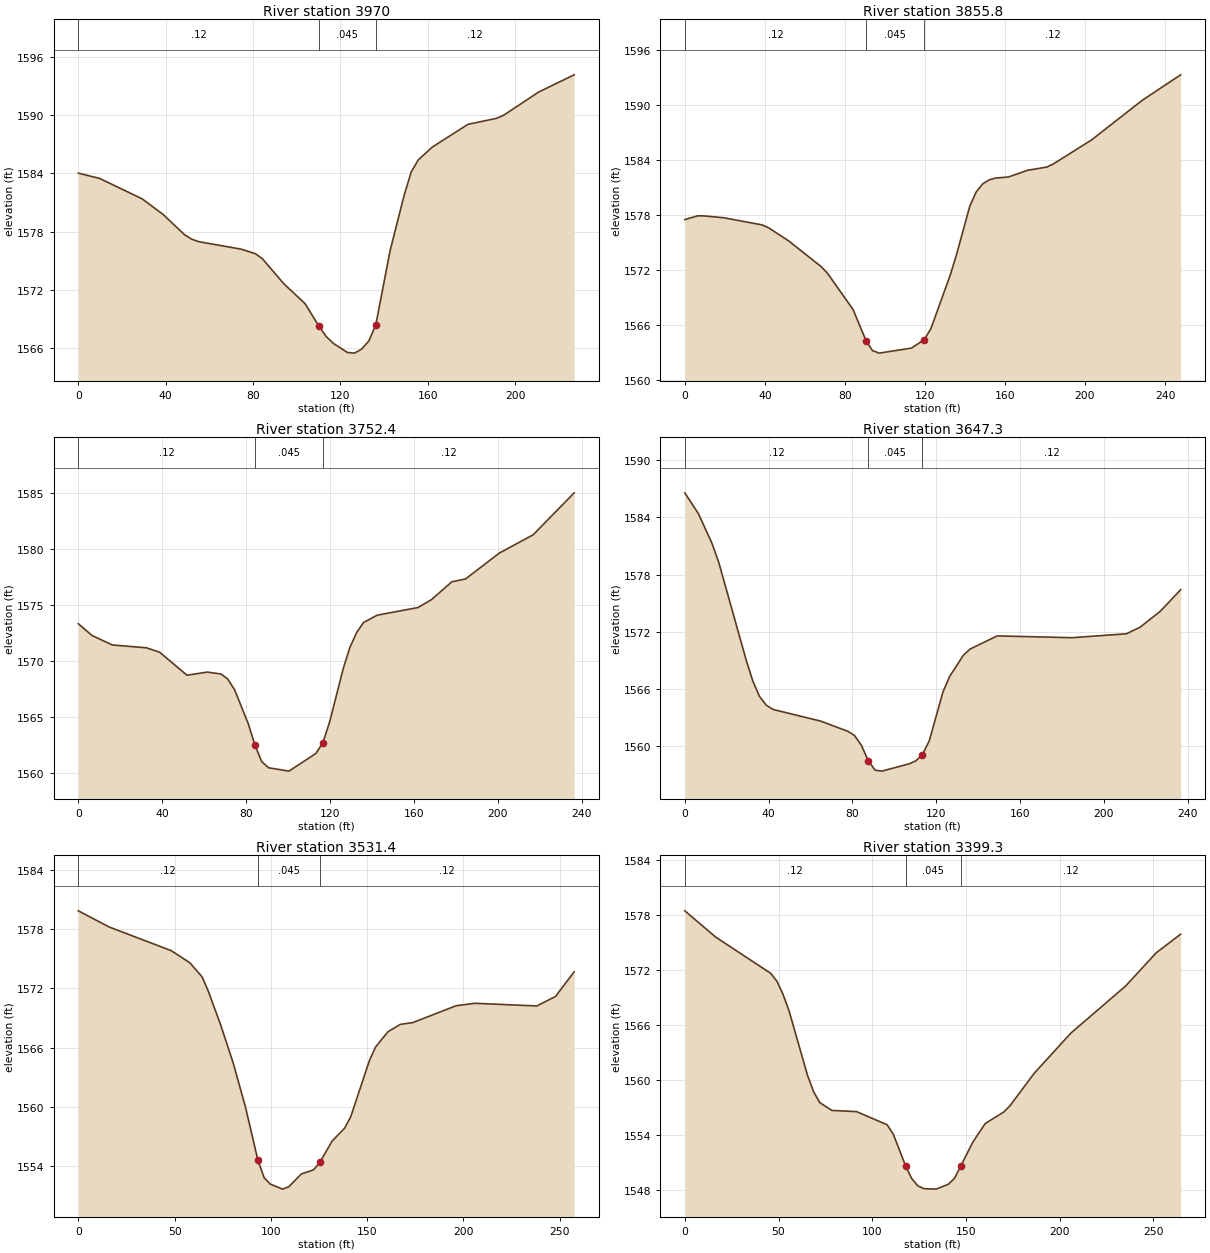
Type RM Length L Ch R = 1 ,3970    ,109.2,114.2,118.7
XS GIS Cut Line= 2
     2038007.632       219519.15     2038201.362      219637.445
#Sta/Elev= 30
       0 1584.03     9.7 1583.49    29.2 1581.38    38.9 1579.75    48.6 1577.68
    51.9 1577.22    55.1 1576.96    74.6 1576.18    81.1 1575.71    84.3 1575.19
      94 1572.63   103.8 1570.56   110.2 1568.22   113.5 1567.16   116.8 1566.45
   123.2 1565.52   126.5 1565.45   129.7 1565.87     133  1566.7   136.2 1568.38
   142.7 1575.99   149.2 1581.78   152.4 1584.15   155.6 1585.39   162.1 1586.73
   178.4 1589.07   191.3 1589.68   194.6 1589.99   210.8 1592.41     227 1594.18
#Mann= 3 ,-1 , 0
       0     .12       0   110.2    .045       0   136.2     .12       0
Bank Sta=110.2,136.2
XS Rating Curve= 0 ,0
Exp/Cntr=0.3,0.1

Type RM Length L Ch R = 1 ,3855.8  ,108.1,103.4,98.5
XS GIS Cut Line= 3
     2037962.688      219607.677     2038086.408      219706.867
     2038175.383      219713.377
#Sta/Elev= 30
       0 1577.52     6.5 1577.93     9.7 1577.92    19.4 1577.72    38.8 1576.93
    42.1 1576.59    51.8 1575.21      68 1572.41    71.2 1571.69    84.1  1567.7
    90.6 1564.28    93.8 1563.22    97.1 1562.94   113.3 1563.49   119.7 1564.42
     123 1565.61   132.7 1571.49   135.9 1573.77   142.4 1578.96   145.6 1580.52
   148.9 1581.42   152.1 1581.85   155.3 1582.05   161.8 1582.17   171.3  1582.9
   180.9 1583.25   184.1 1583.58   203.2  1586.2   228.7 1590.55   247.8 1593.32
#Mann= 3 ,-1 , 0
       0     .12       0    90.6    .045       0   119.7     .12       0
Bank Sta=90.6,119.7
XS Rating Curve= 0 ,0
Exp/Cntr=0.3,0.1

Type RM Length L Ch R = 1 ,3752.4  ,107.7,105.1,102.5
XS GIS Cut Line= 2
     2037913.665      219710.556     2038114.403      219835.339
#Sta/Elev= 30
       0  1573.3     6.5 1572.25    16.2  1571.4    32.4 1571.15    38.8 1570.75
    51.8  1568.7    61.5 1568.98      68 1568.81    71.2 1568.37    74.5 1567.41
      81 1564.38    84.2 1562.47    87.4    1561    90.7 1560.44   100.4 1560.14
   113.3 1561.72   116.6 1562.69   119.8 1564.51   126.3 1569.29   129.5  1571.2
   132.8 1572.54     136 1573.41   142.5 1574.06   161.9 1574.74   168.4 1575.45
   178.1 1577.04   184.6 1577.29   200.7  1579.6   216.9 1581.24   236.4 1584.98
#Mann= 3 ,-1 , 0
       0     .12       0    84.2    .045       0   116.6     .12       0
Bank Sta=84.2,116.6
XS Rating Curve= 0 ,0
Exp/Cntr=0.3,0.1

Type RM Length L Ch R = 1 ,3647.3  ,120.2,115.9,111.5
XS GIS Cut Line= 2
     2037850.804      219802.159     2038059.715      219913.247
#Sta/Elev= 30
       0 1586.56     6.5 1584.38      13 1581.26    16.2 1579.28    29.2 1569.12
    32.4 1566.89    35.6 1565.26    38.9 1564.32    42.1 1563.88    64.8 1562.66
    77.8 1561.59      81 1561.15    84.3 1560.11    87.5 1558.53    90.8 1557.52
      94 1557.42     107 1558.18   110.2 1558.49   113.4 1559.14   116.7 1560.62
   123.2 1565.72   126.4 1567.34   132.9 1569.54   136.1  1570.2   149.1 1571.58
   184.8 1571.39   210.7  1571.8   217.2 1572.48   226.9 1574.16   236.6 1576.41
#Mann= 3 ,-1 , 0
       0     .12       0    87.5    .045       0   113.4     .12       0
Bank Sta=87.5,113.4
XS Rating Curve= 0 ,0
Exp/Cntr=0.3,0.1

Type RM Length L Ch R = 1 ,3531.4  ,107.8,132.1,156.3
XS GIS Cut Line= 3
     2037795.609      219916.936     2037945.349       219975.53
     2038040.835      219960.339
#Sta/Elev= 30
       0 1579.88    16.1 1578.23    48.2 1575.84    57.9 1574.61    64.3 1573.17
    67.5 1571.72      74 1568.25    80.4 1564.45    86.8 1559.96    93.3 1554.53
    96.5 1552.78    99.7 1552.13   106.1 1551.62   109.3 1551.86   115.8 1553.16
   122.2 1553.58   125.4 1554.33   131.8  1556.5   138.3 1557.81   141.5 1558.99
   151.2 1564.69   154.4 1566.06   160.8  1567.6   167.2 1568.35   173.7 1568.53
   196.2 1570.24   205.9 1570.49   238.1 1570.22   247.8 1571.18   257.5 1573.69
#Mann= 3 ,-1 , 0
       0     .12       0    93.3    .045       0   125.4     .12       0
Bank Sta=93.3,125.4
XS Rating Curve= 0 ,0
Exp/Cntr=0.3,0.1

Type RM Length L Ch R = 1 ,3399.3  ,123.6,116.2,108.3
XS GIS Cut Line= 3
     2037761.104      219953.177      2037854.42      220103.134
     2037936.885      220133.516
#Sta/Elev= 30
       0 1578.47    16.4 1575.62    45.8 1571.66    49.1 1570.81    52.3 1569.42
    55.6 1567.58    65.4 1560.58    68.7 1558.76      72 1557.56    78.5 1556.71
    91.6 1556.58   107.9 1555.15   111.2 1554.13   117.8 1550.66     121  1549.3
   124.3 1548.49   127.6 1548.18   134.1 1548.13   140.6 1548.66   143.9 1549.32
   147.2 1550.64   153.7 1553.27   160.3 1555.29   170.1 1556.53   173.4  1557.2
   186.4 1560.76   205.9 1565.13   235.2 1570.28   251.5  1573.9   264.5 1575.92
#Mann= 3 ,-1 , 0
       0     .12       0   117.8    .045       0   147.2     .12       0
Bank Sta=117.8,147.2
XS Rating Curve= 0 ,0
Exp/Cntr=0.3,0.1

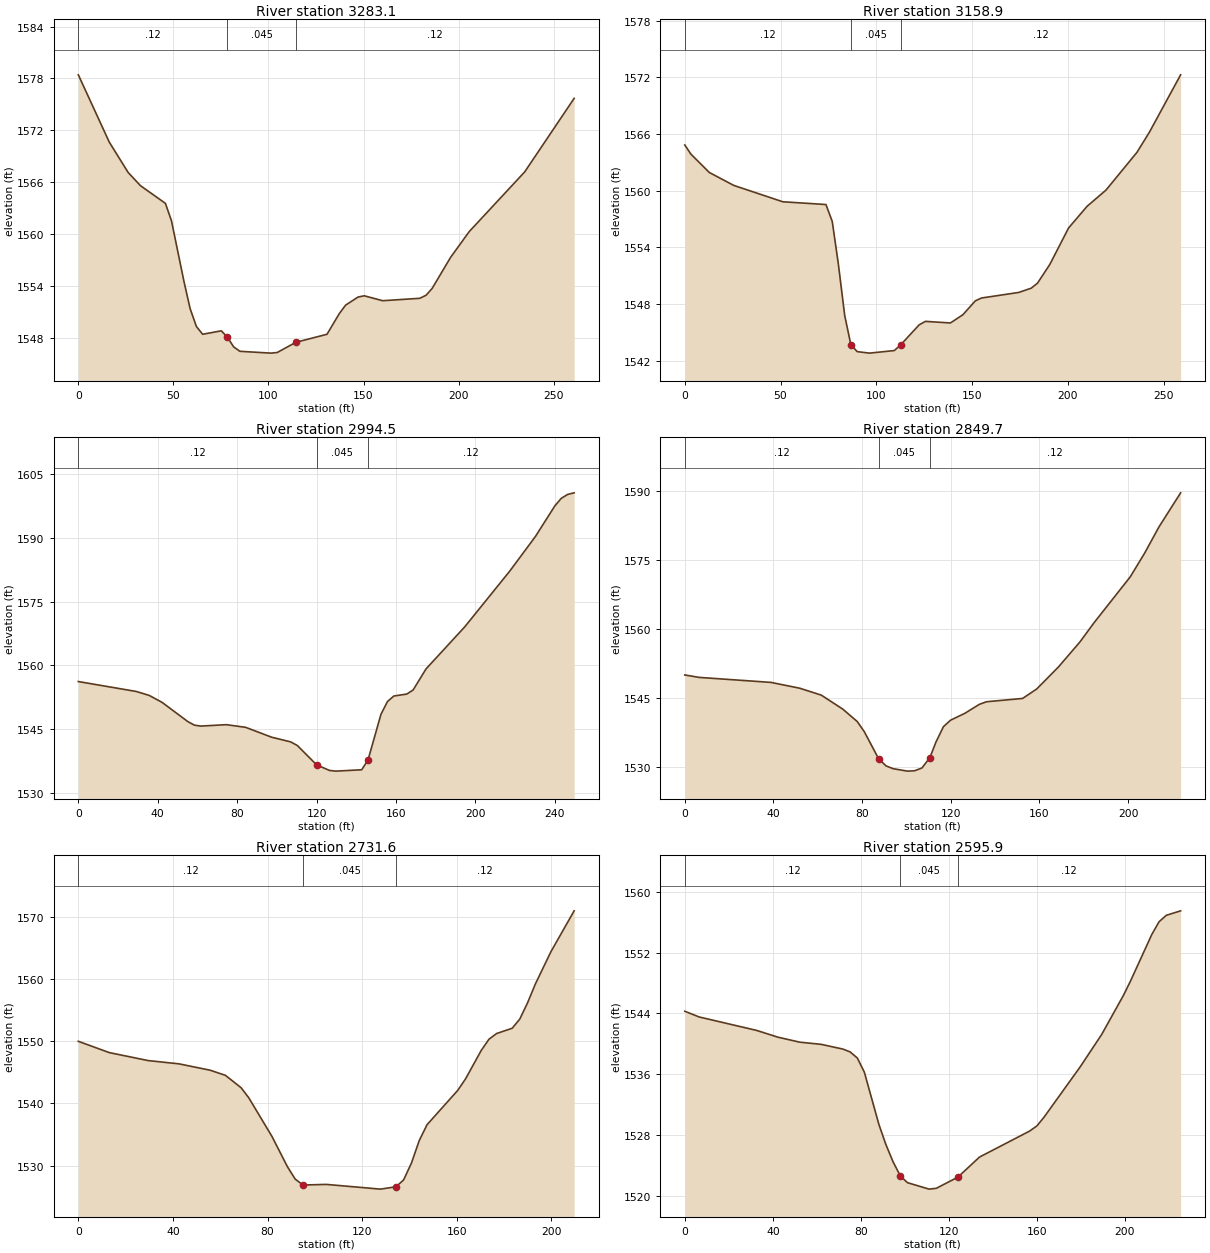
Type RM Length L Ch R = 1 ,3283.1  ,139.7,124.2,105.6
XS GIS Cut Line= 3
     2037669.077      220062.385     2037774.993      220173.663
     2037872.215      220218.802
#Sta/Elev= 30
       0 1578.42    16.3 1570.63    26.2 1567.13    32.7  1565.6    45.8 1563.56
      49 1561.54    55.6 1554.49    58.8 1551.39    62.1 1549.32    65.4 1548.42
    75.2 1548.82    78.4 1548.09    81.7 1546.96      85 1546.45   101.3 1546.24
   104.6 1546.31   114.4 1547.49   130.8 1548.42   137.3 1550.82   140.6 1551.79
   147.1 1552.72   150.4 1552.87   160.1  1552.3   179.6 1552.58   182.9 1552.93
   186.1 1553.72   195.8 1557.31   205.6 1560.29   234.8  1567.2   260.8  1575.7
#Mann= 3 ,-1 , 0
       0     .12       0    78.4    .045       0   114.4     .12       0
Bank Sta=78.4,114.4
XS Rating Curve= 0 ,0
Exp/Cntr=0.3,0.1

Type RM Length L Ch R = 1 ,3158.9  ,160.8,164.4,169.1
XS GIS Cut Line= 3
     2037592.689       220174.74     2037643.699       220223.36
     2037821.651      220285.209
#Sta/Elev= 30
       0 1564.84     3.2 1563.87    12.8 1561.93    25.6 1560.56    51.2 1558.83
    73.7 1558.54      77 1556.75    80.2 1552.22    83.5  1546.8    86.7 1543.72
      90 1542.98    96.4 1542.82   109.4 1543.09   112.7 1543.69   122.4 1545.82
   125.7 1546.18   138.7 1546.01   145.2 1546.88   151.7 1548.35   154.9 1548.65
   174.4 1549.24   180.9 1549.69   184.2 1550.23   190.6  1552.2   200.4 1556.06
   210.1 1558.36   219.9 1560.06   236.1 1564.06   242.6 1566.19   258.9 1572.26
#Mann= 3 ,-1 , 0
       0     .12       0    86.7    .045       0   112.7     .12       0
Bank Sta=86.7,112.7
XS Rating Curve= 0 ,0
Exp/Cntr=0.3,0.1

Type RM Length L Ch R = 1 ,2994.5  ,154.4,144.8,134.2
XS GIS Cut Line= 2
     2037530.154        220331.6     2037752.206      220445.799
#Sta/Elev= 30
       0 1556.17    29.2 1553.83    35.7  1552.9    42.2 1551.26    55.1 1546.75
    58.4 1545.91    61.6 1545.68    74.6 1546.01    84.3 1545.38    97.3 1543.07
     107 1541.95   110.3  1541.1     120 1536.55   126.5 1535.23   129.7 1535.07
   142.7 1535.39   145.9  1537.7   152.4 1548.45   155.7 1551.47   158.9 1552.76
   165.4 1553.22   168.6 1554.18   175.1 1559.14   194.6 1569.05   217.3  1582.2
   230.2 1590.34     240 1597.56   243.2 1599.31   246.4 1600.24   249.7 1600.62
#Mann= 3 ,-1 , 0
       0     .12       0     120    .045       0   145.9     .12       0
Bank Sta=120,145.9
XS Rating Curve= 0 ,0
Exp/Cntr=0.3,0.1

Type RM Length L Ch R = 1 ,2849.7  ,121.3,118.2,115.1
XS GIS Cut Line= 2
     2037480.092      220491.252     2037699.038      220536.945
#Sta/Elev= 30
       0 1550.02     6.5 1549.49    38.9  1548.4    51.9 1547.13    61.6 1545.63
    71.3 1542.58    77.8 1539.89      81 1537.67    87.5 1531.75    90.8 1530.24
      94 1529.63   100.5  1529.1   103.7 1529.18     107 1529.79   110.5 1531.98
   113.4 1535.51   116.7 1538.78   119.9 1540.18   126.4 1541.69   132.9 1543.63
   136.1 1544.19   152.4 1544.91   158.8 1546.98   168.6 1551.77   178.3 1557.22
   184.8 1561.48     201 1571.38   207.5 1576.55   213.9  1582.2   223.7 1589.64
#Mann= 3 ,-1 , 0
       0     .12       0    87.5    .045       0   110.5     .12       0
Bank Sta=87.5,110.5
XS Rating Curve= 0 ,0
Exp/Cntr=0.3,0.1

Type RM Length L Ch R = 1 ,2731.6  ,142.7,135.6,128.3
XS GIS Cut Line= 2
     2037449.091      220613.858     2037656.937      220640.677
#Sta/Elev= 30
       0 1549.99    13.1 1548.17    29.5 1546.89    42.6 1546.36    55.7 1545.34
    62.2 1544.51    68.8 1542.52      72 1540.93    81.9 1534.65    88.4  1529.8
    91.7  1527.8      95 1526.86   104.8 1526.96   127.7  1526.2   134.3 1526.58
   137.5 1527.68   140.8 1530.38   144.1    1534   147.4 1536.56   160.4  1542.1
   163.7 1543.95   170.3 1548.51   173.6 1550.33   176.8 1551.24   183.4 1552.09
   186.6 1553.56   189.9 1556.18   193.2 1559.21   199.8 1564.43   209.6 1570.99
#Mann= 3 ,-1 , 0
       0     .12       0      95    .045       0   134.3     .12       0
Bank Sta=95,134.3
XS Rating Curve= 0 ,0
Exp/Cntr=0.3,0.1

Type RM Length L Ch R = 1 ,2595.9  ,119.3,118.3,117.2
XS GIS Cut Line= 2
     2037444.496      220768.597     2037669.307      220753.959
#Sta/Elev= 30
       0 1544.29     6.5 1543.54    32.6 1541.77    42.4 1540.87    52.2 1540.22
      62 1539.93    71.8 1539.31    75.1 1538.94    78.4 1538.13    81.6 1536.26
    88.2 1529.38    91.4 1526.72    94.7 1524.42      98 1522.57   101.2 1521.71
     111 1520.86   114.3 1520.97   124.1 1522.44   133.9 1525.08   156.7 1528.51
     160 1529.19   163.2 1530.32   179.6 1536.94   189.4 1541.22   199.2 1546.32
   202.4 1548.19   212.2  1554.4   215.5 1556.08   218.8 1556.93   225.3 1557.52
#Mann= 3 ,-1 , 0
       0     .12       0      98    .045       0   124.1     .12       0
Bank Sta=98,124.1
XS Rating Curve= 0 ,0
Exp/Cntr=0.3,0.1