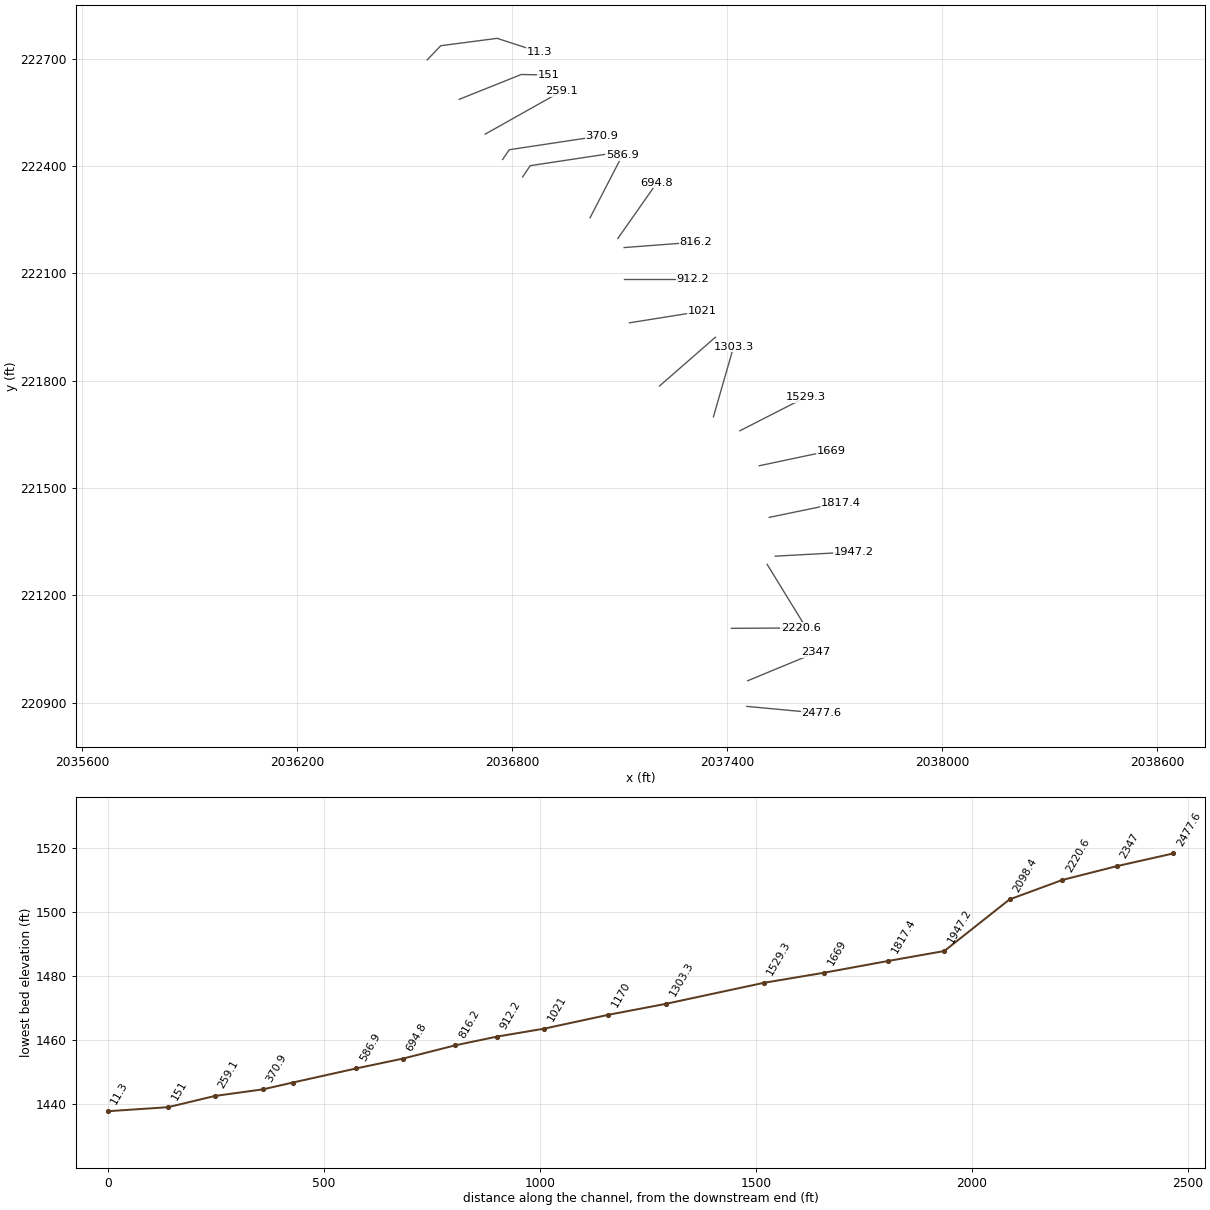
HEC-RAS study LTLSTNYCK.prj: LTLSTNYCK

--- LTLSTNYCK.g01 (geometry) --- (continued)

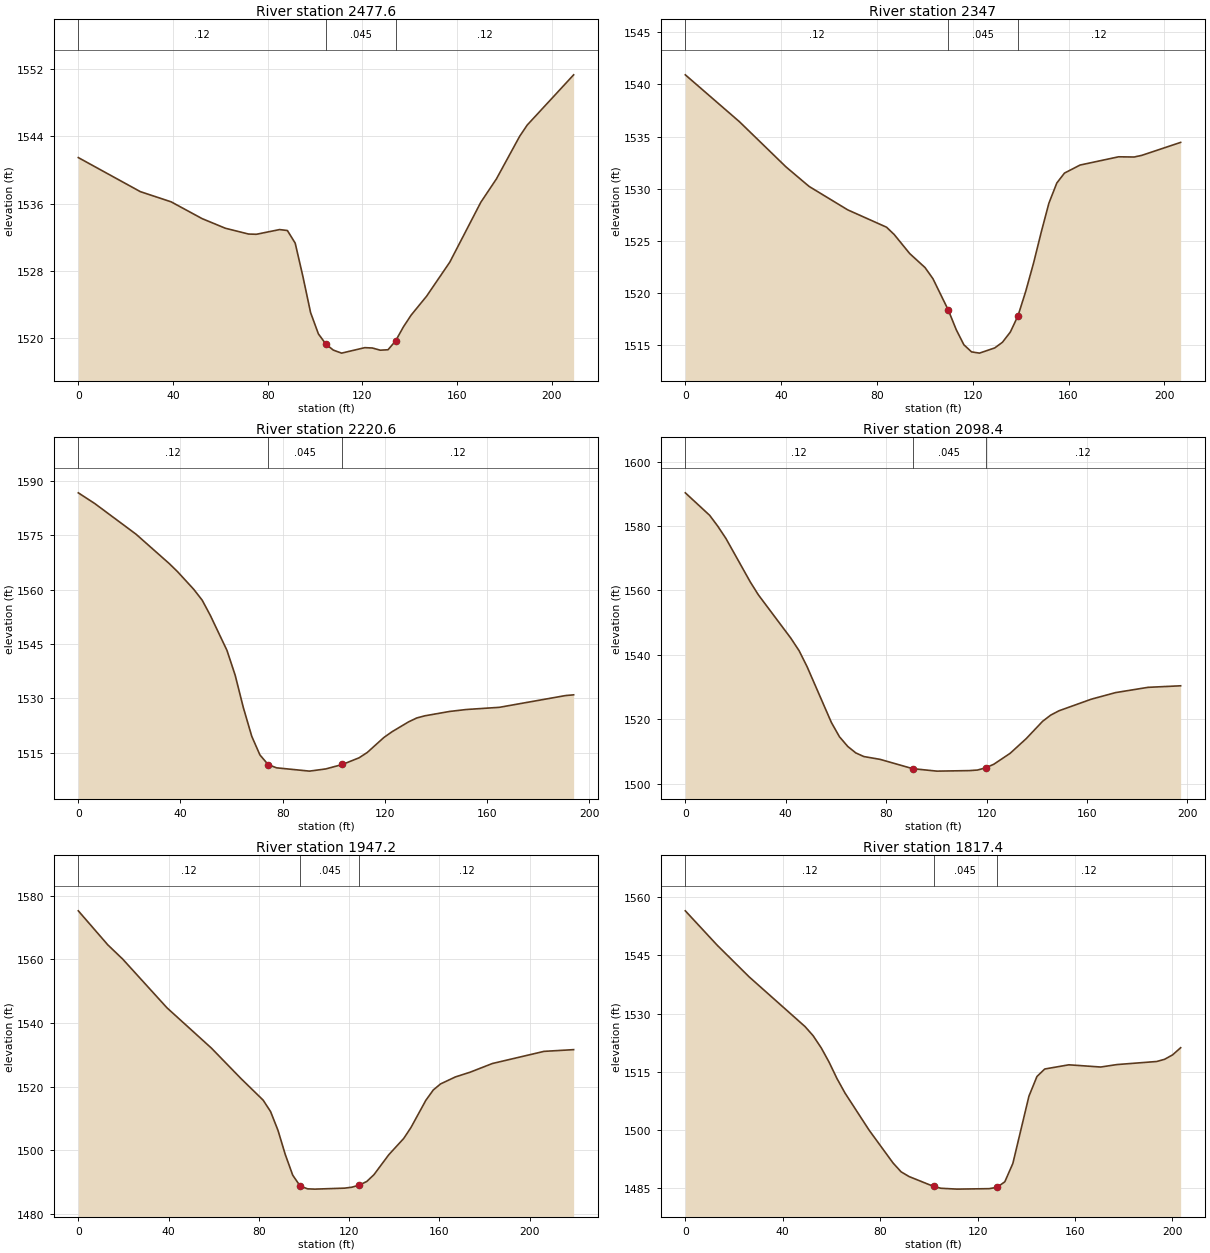
Type RM Length L Ch R = 1 ,2477.6  ,111.3,130.6,149
XS GIS Cut Line= 2
     2037454.897      220889.592     2037663.231      220870.061
#Sta/Elev= 30
       0 1541.47    26.2 1537.42    39.2 1536.21    52.3 1534.21    62.1 1533.07
    71.9 1532.38    75.2 1532.35      85 1532.91    88.3  1532.8    91.6  1531.3
    94.8 1527.41    98.1 1523.04   101.4 1520.51   104.6 1519.28   107.7 1518.58
   111.2 1518.22     121 1518.87   124.2 1518.83   127.5 1518.57   130.8 1518.62
     134 1519.67   137.3 1521.34   140.6 1522.75   147.1 1524.99   156.9 1529.04
     170 1536.16   176.6 1538.94   186.4    1544   189.6 1545.34   209.2 1551.31
#Mann= 3 ,-1 , 0
       0     .12       0   104.6    .045       0     134     .12       0
Bank Sta=104.6,134
XS Rating Curve= 0 ,0
Exp/Cntr=0.3,0.1

Type RM Length L Ch R = 1 ,2347    ,141.1,126.3,111.6
XS GIS Cut Line= 2
     2037457.067      220961.207      2037648.04      221040.417
#Sta/Elev= 30
       0 1540.91    22.6 1536.42      42  1532.1    51.7 1530.22    67.8 1527.98
      84 1526.32    87.2 1525.62    93.7 1523.79   100.1 1522.45   103.4 1521.38
   109.8 1518.38   113.1 1516.51   116.3 1515.06   119.5 1514.38   122.8 1514.26
   129.2 1514.76   132.4  1515.3   135.7 1516.28   138.9 1517.84   142.1 1520.16
   145.4 1522.89   148.6 1525.85   151.8 1528.62   155.1 1530.55   158.3  1531.5
   164.8 1532.27   180.9 1533.06   187.4 1533.04   190.6  1533.2   206.8 1534.44
#Mann= 3 ,-1 , 0
       0     .12       0   109.8    .045       0   138.9     .12       0
Bank Sta=109.8,138.9
XS Rating Curve= 0 ,0
Exp/Cntr=0.3,0.1

Type RM Length L Ch R = 1 ,2220.6  ,160.8,122.3,83.1
XS GIS Cut Line= 2
     2037411.836      221107.831     2037605.722      221108.776
#Sta/Elev= 30
       0 1586.64     6.5 1583.66    22.6 1575.24    35.6 1567.14    38.8 1564.95
    45.2 1560.04    48.5 1557.05    51.7 1552.84    58.2 1543.21    61.4  1536.4
    64.6 1527.47    67.9 1519.54    71.1 1514.41    74.3 1511.76    77.6 1510.86
    90.5 1509.95    96.9 1510.56   103.4 1511.79   109.9 1513.62   113.1 1515.08
   119.6 1519.21   122.8  1520.8   129.3 1523.53   132.5  1524.6   135.7  1525.2
   145.4  1526.4   151.9 1526.93   164.8 1527.53   190.7 1530.77   193.9 1530.97
#Mann= 3 ,-1 , 0
       0     .12       0    74.3    .045       0   103.4     .12       0
Bank Sta=74.3,103.4
XS Rating Curve= 0 ,0
Exp/Cntr=0.3,0.1

Type RM Length L Ch R = 1 ,2098.4  ,108.3,151.1,192.3
XS GIS Cut Line= 2
     2037511.321      221286.728     2037614.403      221118.542
#Sta/Elev= 30
       0 1590.31     9.7 1583.32    12.9 1579.98    16.2 1576.11    25.9  1562.6
    29.1 1558.63      42  1545.2    45.3 1541.31    48.5 1536.32    58.2 1518.96
    61.4 1514.55    64.7 1511.55    67.9 1509.54    71.1 1508.41    77.6 1507.53
    90.6 1504.64   100.2 1503.88   113.2 1504.04   116.4 1504.22   119.6 1504.89
   122.9 1506.03   129.4 1509.42   135.8 1513.98   142.3 1519.34   145.5 1521.25
   148.8 1522.61   161.7 1526.22   171.4 1528.27   184.3  1529.9   197.3 1530.38
#Mann= 3 ,-1 , 0
       0     .12       0    90.6    .045       0   119.6     .12       0
Bank Sta=90.6,119.6
XS Rating Curve= 0 ,0
Exp/Cntr=0.3,0.1

Type RM Length L Ch R = 1 ,1947.2  ,125,129.9,134.6
XS GIS Cut Line= 2
     2037534.107      221309.514     2037753.291       221321.45
#Sta/Elev= 30
       0  1575.3    13.1 1564.58    19.7  1560.1    39.3  1544.8      59 1532.12
    72.1 1522.55    81.9 1515.78    85.2 1512.19    88.5 1506.24    91.7 1498.71
      95  1492.2    98.3 1488.77   101.6 1487.88   104.8 1487.79     118  1488.1
   121.2 1488.39   124.5 1489.06   127.8 1490.18     131 1492.32   137.6 1498.62
   144.2 1503.72   147.4 1507.15     154 1515.71   157.3 1518.96   160.5 1520.86
   167.1 1523.07   173.6 1524.55   183.5 1527.29   206.4 1531.11   219.5 1531.65
#Mann= 3 ,-1 , 0
       0     .12       0    98.3    .045       0   124.5     .12       0
Bank Sta=98.3,124.5
XS Rating Curve= 0 ,0
Exp/Cntr=0.3,0.1

Type RM Length L Ch R = 1 ,1817.4  ,148,148.4,148.3
XS GIS Cut Line= 2
     2037517.232      221417.937     2037716.399      221459.254
#Sta/Elev= 30
       0 1556.53    13.1 1547.65    26.2 1539.49    49.2 1526.63    52.5 1524.28
    55.8 1521.17      59 1517.51    62.3 1513.21    65.6 1509.47    75.5 1499.89
    85.3 1491.44    88.6 1489.16    91.9 1487.93     102 1485.38     105 1484.91
   111.6 1484.69   124.7 1484.81     128 1485.15   131.2 1486.59   134.5 1491.32
   141.1 1508.68   144.4 1513.77   147.6  1515.7   157.5 1516.78   170.6 1516.21
   177.2 1516.84   193.6 1517.64   196.8  1518.2   200.1 1519.35   203.4 1521.19
#Mann= 3 ,-1 , 0
       0     .12       0     102    .045       0     128     .12       0
Bank Sta=102,128
XS Rating Curve= 0 ,0
Exp/Cntr=0.3,0.1

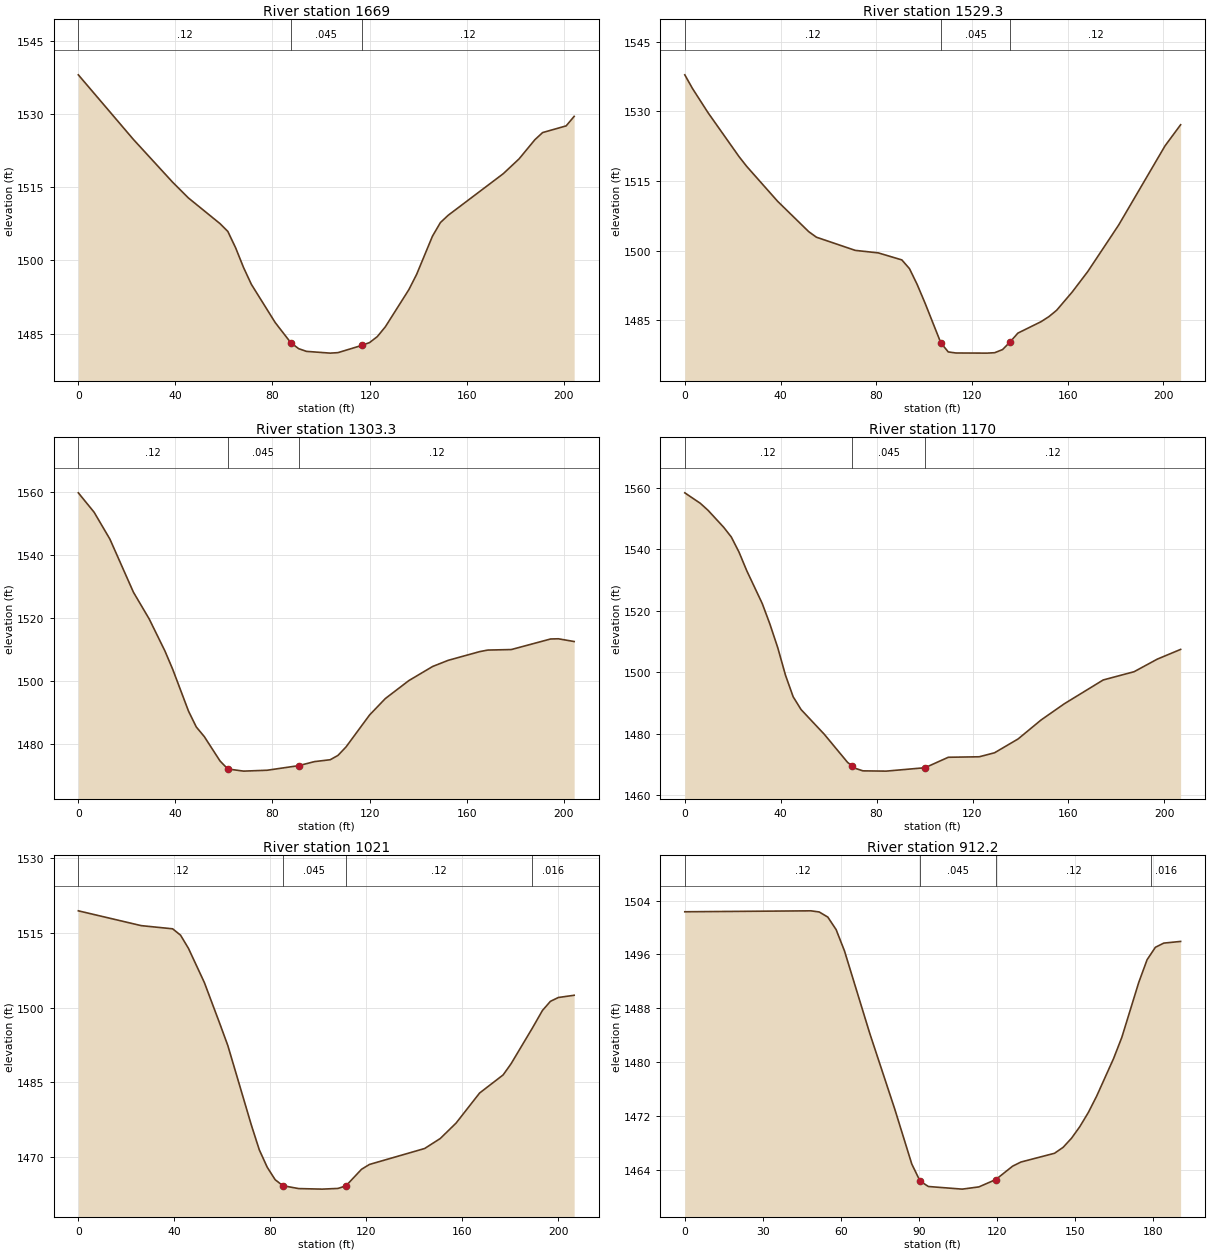
Type RM Length L Ch R = 1 ,1669    ,129.4,139.7,149.3
XS GIS Cut Line= 2
     2037489.437      221562.264     2037689.272      221604.653
#Sta/Elev= 30
       0 1538.03    22.7 1524.79    38.9 1516.01    45.4 1512.79    58.4 1507.54
    61.6 1505.95    64.8 1502.61    68.1 1498.53    71.3 1495.11    81.1  1487.3
    87.6 1483.12    90.8 1481.93      94 1481.38   103.8 1481.02     107 1481.12
   116.7 1482.59     120 1483.18   123.2 1484.41   126.5 1486.41   136.2 1494.03
   139.4 1497.16   145.9 1504.96   149.2 1507.77   152.4 1509.26   175.1 1517.78
   181.6 1520.81   188.1 1524.73   191.3  1526.2     201 1527.57   204.3 1529.52
#Mann= 3 ,-1 , 0
       0     .12       0    87.6    .045       0   116.7     .12       0
Bank Sta=87.6,116.7
XS Rating Curve= 0 ,0
Exp/Cntr=0.3,0.1

Type RM Length L Ch R = 1 ,1529.3  ,176.8,226,260.4
XS GIS Cut Line= 2
     2037435.366      221659.992     2037619.828      221754.393
#Sta/Elev= 30
       0 1537.91     3.2 1534.97     9.7 1529.75    22.7 1520.24    25.9 1518.14
    38.8 1510.62    51.8 1504.07      55 1502.88    71.2 1500.04    80.9 1499.49
    90.7 1497.98    93.9 1496.09    97.1 1492.69   100.4 1488.66     107 1480.08
   110.1 1478.13   113.3  1477.9   126.3 1477.87   129.5 1477.96   132.8 1478.64
     136 1480.32   139.2 1482.19   148.9 1484.66   152.2 1485.76   155.4 1487.12
   161.9 1491.06   168.4 1495.47   181.3  1505.5   200.7  1522.6   207.2 1527.14
#Mann= 3 ,-1 , 0
       0     .12       0     107    .045       0     136     .12       0
Bank Sta=107,136
XS Rating Curve= 0 ,0
Exp/Cntr=0.3,0.1

Type RM Length L Ch R = 1 ,1303.3  ,154.6,133.3,111.9
XS GIS Cut Line= 2
     2037361.581      221699.054     2037418.005      221895.452
#Sta/Elev= 30
       0 1559.72     6.5 1553.56      13 1545.03    22.7 1528.16    29.2 1519.66
    35.7 1509.46    38.9 1503.65    45.4 1490.39    48.6 1485.36    51.9  1482.3
    58.4 1474.54    61.6 1472.01    68.1 1471.33    77.8 1471.61    90.8 1473.07
    97.3 1474.35   103.8 1474.95     107 1476.33   110.3 1479.01     120 1489.16
   126.5 1494.38   136.2 1500.09     146 1504.57   152.4 1506.52   165.4 1509.29
   168.7 1509.78   178.4 1509.94   194.6  1513.3   197.8 1513.36   204.3 1512.49
#Mann= 3 ,-1 , 0
       0     .12       0    61.6    .045       0    90.8     .12       0
Bank Sta=61.6,90.8
XS Rating Curve= 0 ,0
Exp/Cntr=0.3,0.1

Type RM Length L Ch R = 1 ,1170    ,170,149,127.3
XS GIS Cut Line= 2
     2037211.371      221785.312     2037367.007      221921.493
#Sta/Elev= 30
       0 1558.29     6.5 1554.87     9.7 1552.61    16.2 1547.12    19.4 1543.94
    22.6 1539.06    25.8 1533.07    32.3 1522.34    35.5 1515.66    38.8 1507.92
      42 1499.06    45.2 1492.05    48.5  1487.9    58.2 1479.86    67.9 1470.74
    69.7 1469.66    71.1 1468.82    74.3    1468      84 1467.91   100.2 1469.02
   109.9 1472.41   122.8 1472.57   129.2 1473.87     139 1478.35   148.6 1484.52
   158.3 1489.79   174.5 1497.51   187.4  1500.2   197.1 1504.29   206.8 1507.44
#Mann= 3 ,-1 , 0
       0     .12       0    69.7    .045       0   100.2     .12       0
Bank Sta=69.7,100.2
XS Rating Curve= 0 ,0
Exp/Cntr=0.3,0.1

Type RM Length L Ch R = 1 ,1021    ,114.8,108.8,102.7
XS GIS Cut Line= 2
     2037127.237      221961.776     2037331.199       221994.41
#Sta/Elev= 30
       0 1519.41    26.2 1516.44    39.3  1515.8    42.6 1514.52    45.9 1511.87
    52.5 1505.04      59 1496.71    62.3 1492.37    72.1 1476.42    75.4 1471.47
    78.7 1467.98      82 1465.48    85.2 1464.27    91.8 1463.69   101.6 1463.58
   108.2 1463.72   111.5 1464.23     118 1467.56   121.3 1468.53   144.3 1471.73
   150.8 1473.73   157.4 1476.83   167.2 1482.86     177 1486.49   180.3 1488.72
  189.191495.889   193.4 1499.43   196.7 1501.25     200 1502.02   206.6 1502.47
#Mann= 4 ,-1 , 0
       0     .12       0    85.2    .045       0   111.5     .12       0
  189.19    .016       0
Bank Sta=85.2,111.5
XS Rating Curve= 0 ,0
Exp/Cntr=0.3,0.1

Type RM Length L Ch R = 1 ,912.2   ,93.1,96,98.8
XS GIS Cut Line= 2
     2037112.573      222084.254     2037303.291      222084.254
#Sta/Elev= 30
       0 1502.34    48.5 1502.48    51.7 1502.31      55 1501.55    58.2 1499.69
    61.4 1496.54    71.1 1484.31    80.8 1472.95    87.3 1464.84    90.5  1462.3
    93.7  1461.5   106.7 1461.11   113.1 1461.44   119.6 1462.53   126.1 1464.53
   129.3 1465.14   142.2 1466.44   145.5 1467.32   148.7 1468.66   151.9 1470.38
   155.2  1472.5   158.4 1474.93   164.9 1480.51   168.1 1483.69   174.6 1491.84
   177.8 1495.21  179.421496.147     181 1497.06   184.2 1497.68   190.7 1497.93
#Mann= 4 ,-1 , 0
       0     .12       0    90.5    .045       0   119.6     .12       0
  179.42    .016       0
Bank Sta=90.5,119.6
XS Rating Curve= 0 ,0
Exp/Cntr=0.3,0.1

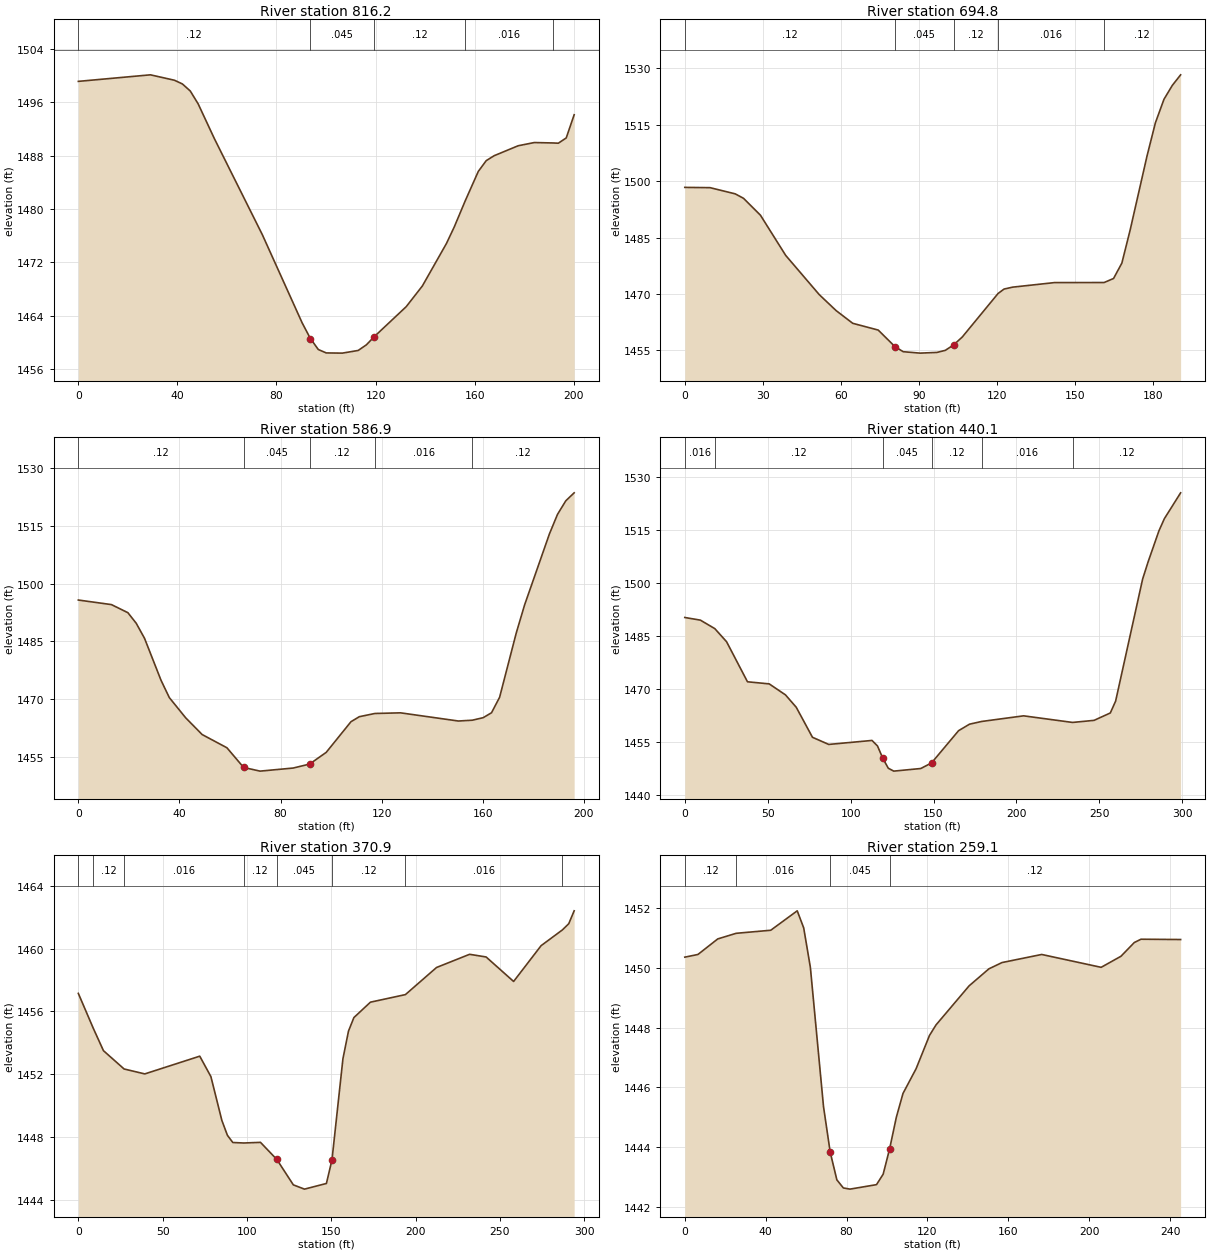
Type RM Length L Ch R = 1 ,816.2   ,88,121.4,154.8
XS GIS Cut Line= 2
     2037112.449      222172.144     2037312.102      222187.335
#Sta/Elev= 30
       0  1499.1    29.1 1500.08    38.8 1499.27      42 1498.72    45.2 1497.66
    48.4 1495.72    54.9 1490.55    74.3 1476.14    90.4 1462.92    93.7  1460.6
    96.9 1458.95   100.1 1458.44   106.6 1458.41     113 1458.81   116.3 1459.65
   119.5 1460.88   132.4 1465.37   138.9 1468.46   148.6  1474.8   151.8 1477.31
  156.231481.225   161.5 1485.62   164.7 1487.23   167.9 1487.97   177.6 1489.46
   184.1 1489.94  191.781489.877   193.8 1489.84     197 1490.63   200.2  1494.1
#Mann= 5 ,-1 , 0
       0     .12       0    93.7    .045       0   119.5     .12       0
  156.23    .016       0  191.78     .12       0
Bank Sta=93.7,119.5
XS Rating Curve= 0 ,0
Exp/Cntr=0.3,0.1

Type RM Length L Ch R = 1 ,694.8   ,102.6,107.9,112.8
XS GIS Cut Line= 2
     2037094.958      222197.535     2037204.333      222353.785
#Sta/Elev= 30
       0 1498.34     9.7 1498.27    19.4 1496.62    22.6 1495.43    29.1 1490.94
    38.8 1480.26    51.7 1469.83    58.2 1465.57    64.6 1462.19    74.4 1460.39
    80.8 1456.01      84 1454.64    90.5 1454.26      97 1454.45   100.2    1455
   103.4 1456.45   106.7 1458.53  120.491470.123   122.8  1471.3   126.1 1471.81
   142.2 1473.02  161.271473.038   164.9 1474.11   168.1  1478.2   171.3 1487.04
   177.8 1506.76     181 1515.52   184.3 1521.78   187.5 1525.47   190.7 1528.28
#Mann= 5 ,-1 , 0
       0     .12       0    80.8    .045       0   103.4     .12       0
  120.49    .016       0  161.27     .12       0
Bank Sta=80.8,103.4
XS Rating Curve= 0 ,0
Exp/Cntr=0.3,0.1

Type RM Length L Ch R = 1 ,586.9   ,187.7,146.8,105.1
XS GIS Cut Line= 2
     2037017.599      222255.587     2037107.458      222429.957
#Sta/Elev= 30
       0 1495.73    13.1 1494.54    19.6 1492.44    22.9 1489.69    26.2 1485.76
    32.7 1474.88      36 1470.34    42.5 1465.06      49 1460.72    58.8 1457.28
    65.4 1452.16    71.9  1451.2      85    1452    91.5 1453.03    98.1 1456.09
   107.9 1464.07   111.2 1465.37  117.351466.202   127.5 1466.37   150.4 1464.24
  155.911464.453   160.2 1465.11   163.5 1466.39   166.7 1470.42   173.3 1487.18
   176.6 1494.48   186.4 1512.91   189.6 1518.01   192.9 1521.56   196.2 1523.63
#Mann= 5 ,-1 , 0
       0     .12       0    65.4    .045       0    91.5     .12       0
  117.35    .016       0  155.91     .12       0
Bank Sta=65.4,91.5
XS Rating Curve= 0 ,0
Exp/Cntr=0.3,0.1

Type RM Length L Ch R = 1 ,440.1   ,70.1,69.2,70.1
XS GIS Cut Line= 3
     2036829.372      222369.745     2036850.514      222401.094
      2037108.76      222440.157
#Sta/Elev= 30
       0 1490.26     9.4 1489.51    18.11487.107    25.2  1483.4    37.8 1472.07
    50.9 1471.48    60.7 1468.37    67.2 1464.87      77 1456.37    86.8 1454.35
   112.9 1455.48   116.2 1453.92   119.4 1450.44   122.7 1447.63     126  1446.8
   142.3 1447.54   148.8 1449.12   165.1 1458.24   171.7 1460.08  178.981460.844
   204.3 1462.44  233.851460.572   246.8 1461.16   256.6 1463.25   259.8  1466.6
   276.1 1501.15   279.4    1506   285.9 1514.74   289.2 1518.21     299 1525.52
#Mann= 6 ,-1 , 0
       0    .016       0    18.1     .12       0   119.4    .045       0
   148.8     .12       0  178.98    .016       0  233.85     .12       0
Bank Sta=119.4,148.8
XS Rating Curve= 0 ,0
Exp/Cntr=0.3,0.1

Type RM Length L Ch R = 1 ,370.9   ,91.9,111.7,130
XS GIS Cut Line= 3
     2036773.549      222418.342      2036791.92      222445.582
     2037050.166      222484.644
#Sta/Elev= 30
       0 1457.15    8.811454.941    14.9  1453.5   27.141452.334    39.4 1452.02
      72 1453.15    78.6 1451.85    85.1 1449.06    88.4 1448.11    91.6 1447.65
   98.131447.619     108 1447.66   117.7 1446.57   127.5 1444.95   134.1 1444.68
   147.1 1445.04   150.4 1446.54   156.9 1452.99   160.2 1454.75   163.4 1455.61
   173.2 1456.59  193.951457.073   212.4  1458.8     232 1459.64   241.8 1459.47
   258.1 1457.91   274.4 1460.19  287.051461.196   290.8 1461.59     294 1462.41
#Mann= 8 ,-1 , 0
       0    .016       0    8.81     .12       0   27.14    .016       0
   98.13     .12       0   117.7    .045       0   150.4     .12       0
  193.95    .016       0  287.05     .12       0
Bank Sta=117.7,150.4
XS Rating Curve= 0 ,0
Exp/Cntr=0.3,0.1

Type RM Length L Ch R = 1 ,259.1   ,113,108.2,103.7
XS GIS Cut Line= 2
     2036724.803      222489.102     2036938.404      222609.427
#Sta/Elev= 30
       0 1450.36     6.5 1450.45    16.3 1450.97    25.41451.158    42.5 1451.26
    55.6 1451.91    58.8 1451.34    62.1 1450.02    68.6 1445.36    71.9 1443.84
    75.2 1442.91    78.4 1442.64    81.7  1442.6    94.8 1442.75    98.1  1443.1
   101.3 1443.95   104.6    1445   107.9  1445.8   114.4 1446.63     121 1447.74
   124.2 1448.09   140.6  1449.4   150.4 1449.97   156.9 1450.18   176.5 1450.45
   205.9 1450.02   215.7 1450.39   222.3 1450.85   225.6 1450.96   245.2 1450.95
#Mann= 4 ,-1 , 0
       0     .12       0    25.4    .016       0    71.9    .045       0
   101.3     .12       0
Bank Sta=71.9,101.3
XS Rating Curve= 0 ,0
Exp/Cntr=0.3,0.1

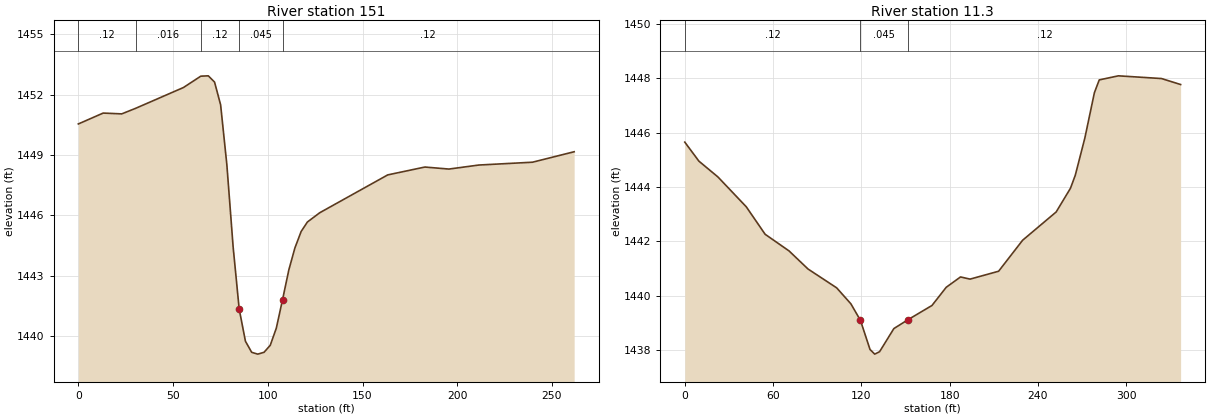
Type RM Length L Ch R = 1 ,151     ,149.5,139.6,129.7
XS GIS Cut Line= 3
     2036652.609      222586.534     2036825.427      222655.868
     2036900.948      222654.566
#Sta/Elev= 30
       0 1450.54    13.1 1451.08    22.9 1451.04   30.271451.317    55.5 1452.35
   64.641452.913    68.6 1452.93    71.9 1452.62    75.1 1451.49    78.4 1448.51
    81.7 1444.44    84.9 1441.35    88.2 1439.75    91.5  1439.2    94.7 1439.11
      98  1439.2   101.3 1439.55   104.5  1440.4   107.8 1441.82   111.1 1443.29
   114.3 1444.38   117.6  1445.2   120.9 1445.67   127.4 1446.13   163.3 1448.01
   182.9  1448.4   195.6  1448.3   211.4  1448.5   239.7 1448.64   261.7 1449.16
#Mann= 5 ,-1 , 0
       0     .12       0   30.27    .016       0   64.64     .12       0
    84.9    .045       0   107.8     .12       0
Bank Sta=84.9,107.8
XS Rating Curve= 0 ,0
Exp/Cntr=0.3,0.1

Type RM Length L Ch R = 1 ,11.3    ,0,11.3,24.6
XS GIS Cut Line= 4
     2036563.244      222696.814     2036600.948       222736.38
     2036758.283      222756.997     2036875.831      222718.666
#Sta/Elev= 30
       0 1445.65     9.6 1444.95    22.5 1444.37    41.8 1443.27    54.6 1442.26
    70.8 1441.65    83.8 1440.98   103.2 1440.29   112.9  1439.7   119.4 1439.09
   125.9 1438.02   129.1 1437.85   132.4 1437.94   142.1 1438.79   151.8 1439.12
     168 1439.64   177.7 1440.31   187.4 1440.69   193.9 1440.61   213.3  1440.9
   229.6 1442.04   252.4 1443.08   262.1 1443.95   265.4 1444.43   271.9  1445.8
   278.4 1447.47   281.7 1447.94   294.7 1448.09     324 1447.99     337 1447.77
#Mann= 3 ,-1 , 0
       0     .12       0   119.4    .045       0   151.8     .12       0
Bank Sta=119.4,151.8
XS Rating Curve= 0 ,0
Exp/Cntr=0.3,0.1

Chan Stop Cuts=-1
Use User Specified Reach Order=0
Composite Channel Slope=5